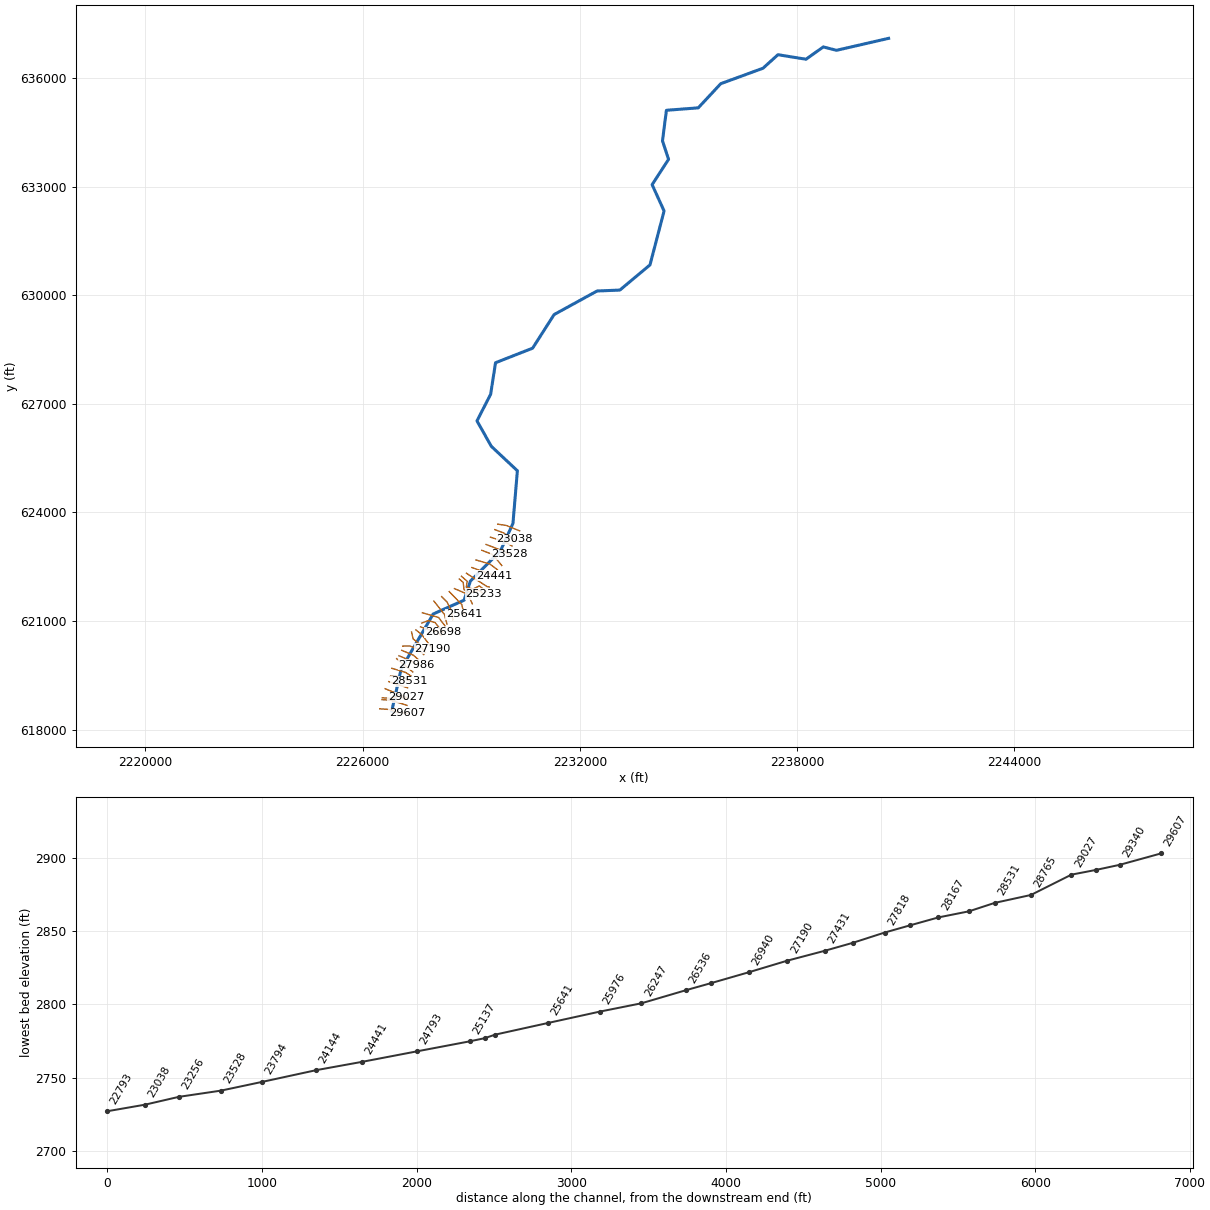
--- BIRCHFK.prj (project) ---

Proj Title=BIRCHFK
Current Plan=p01
Default Exp/Contr=0,0
English Units
Geom File=g01
Flow File=f01
Plan File=p01
BEGIN DESCRIPTION:
----------MODEL BY WOOD PLC 2022----------
AFH study
Randolph County, WV
HEC-RAS Version: RAS 6.2
Vertical Datum: NAVD88
Projection: NAD 1983 StatePlane West Virginia S FIPS 4702 (US Feet)
Terrain: 1-meter LIDAR (FEMA Region III 3DEP collected 2016-2018)
Land Use: 2019 NLCD
Hydrologic Method:
WV SIR2010-5033 regression equations
Additional Model Notes:
KWSE with MIDFKRIV due to name change at confluence
END DESCRIPTION:
DSS Export Rating Curves= 0
DSS Export Rating Curve Sorted= 0
DSS Export Volume Flow Curves= 0
DXF OffsetX= 0
DXF OffsetY= 0
DXF ScaleX= 0
DXF ScaleY= 0

--- BIRCHFK.p01 (plan) ---

Plan Title=Floodplain
Program Version=6.20
Short Identifier=Floodplain
Geom File=g01
Flow File=f01
Subcritical Flow
K Sum by GR= 0
Std Step Tol= 0.01
Critical Tol= 0.01
Num of Std Step Trials= 20
Max Error Tol= 0.3
Flow Tol Ratio= 0.001
Split Flow NTrial= 30
Split Flow Tol= 0.02
Split Flow Ratio= 0.02
Log Output Level= 0
Friction Slope Method= 1
Unsteady Friction Slope Method= 2
Unsteady Bridges Friction Slope Method= 1
Parabolic Critical Depth
Global Vel Dist= 0 , 0 , 0
Global Log Level= 0
CheckData=True
Encroach Param=-1 ,0,0, 0
Mapping Interval=1HOUR
Computation Time Step Use Courant=        0
Computation Time Step Use Time Series=    0
Computation Time Step Count To Double=0
Computation Time Step Max Doubling=0
Computation Time Step Max Halving=0
Computation Time Step Residence Courant=0
Run HTab= 0
Run UNet= 0
Run Sediment= 0
Run PostProcess= 0
Run WQNet= 0
Run RASMapper=-1
UNET Theta= 0
UNET Theta Warmup= 0
UNET ZTol= 0
UNET ZSATol= 0
UNET MxIter= 0
UNET Max Iter WO Improvement= 0
UNET MaxInSteps= 0
UNET DtIC= 0
UNET DtMin= 0
UNET MaxCRTS= 0
UNET WFStab= 0
UNET SFStab= 0
UNET WFX= 1
UNET SFX= 1
UNET Gravity=32.174
UNET 1D Methodology=Finite Difference
UNET DSS MLevel= 1
UNET Pardiso=0
UNET DZMax Abort= 0
UNET Use Existing IB Tables= 0
UNET Froude Reduction=False
UNET Froude Limit= 0
UNET Froude Power= 0
UNET D1 Cores= 0
UNET WindReference=Eulerian
UNET WindDragFormulation=Hsu (1988)
UNET D2 Coriolis=0
UNET D2 Cores= 0
UNET D2 Theta= 1
UNET D2 Theta Warmup= 1
UNET D2 Z Tol= 0.01
UNET D2 Volume Tol= 0.01
UNET D2 Max Iterations= 20
UNET D2 Equation= 0
UNET D2 RampUpFraction=0.1
UNET D2 TimeSlices= 1
UNET D2 Turbulence Formulation=Non-Conservative (original)
UNET D2 Eddy Viscosity=0.3
UNET D2 Transverse Eddy Viscosity=0.1
UNET D2 Smagorinsky Mixing=0
UNET D2 BCVolumeCheck=0
UNET D2 Cores=0
UNET D2 SolverType=PARDISO (Direct)
UNET D2 Minimum Iterations= 2147483647
UNET D2 Maximum Iterations= 2147483647
UNET D2 Restart Number= 10
UNET D2 Relaxation Coeff=1.3
UNET D2 SOR Precondition Iterations= 10
UNET D2 ILUT Maximum Fill= 8
UNET D2 ILUT Tolerance=1E-08
UNET D1D2 MaxIter= 0
UNET D1D2 ZTol=0.01
UNET D1D2 QTol=0.1
UNET D1D2 MinQTol=1
Write IC File= 0
Write IC File at Fixed DateTime=0
Write IC File at Sim End=0
Echo Input=False
Echo Parameters=False
Echo Output=False
Write Detailed= 0
HDF Write Warmup=0
HDF Write Time Slices=0
HDF Flush=0
HDF Compression= 1
HDF Chunk Size= 1
HDF Spatial Parts= 1
HDF Use Max Rows=0
HDF Fixed Rows= 1
Calibration Method= 0
Calibration Iterations= 20
Calibration Max Change=0.05
Calibration Tolerance=0.2
Calibration Maximum=1.5
Calibration Minimum=0.5
Calibration Optimization Method= 1
WQ AD Non Conservative
WQ ULTIMATE=-1
WQ Max Comp Step=1HOUR
WQ Output Interval=15MIN
WQ Output Selected Increments= 0
WQ Output face flow=0
WQ Output face velocity=0
WQ Output face area=0
WQ Output face dispersion=0
WQ Output cell volume=0
WQ Output cell surface area=0
WQ Output cell continuity=0
WQ Output cumulative cell continuity=0
WQ Output face conc=0
WQ Output face dconc_dx=0
WQ Output face courant=0
WQ Output face peclet=0
WQ Output face adv mass=0
WQ Output face disp mass=0
WQ Output cell mass=0
WQ Output cell source sink temp=0
WQ Output nsm pathways=0
WQ Output nsm derived pathways=0
WQ Create Restart=0
WQ Fixed Restart=0
WQ System Summary=0
WQ Write To DSS=0
Sorting and Armoring Iterations= 10
XS Update Threshold= 0.02
Bed Roughness Predictor= 0
Hydraulics Update Threshold= 0.02
Energy Slope Method= 1
Volume Change Method= 1
Sediment Retention Method= 0
Sediment TS Multiplier= 1
Warm Up Method= 0
XS Weighting Method= 0
Number of US Weighted Cross Sections= 1
Number of DS Weighted Cross Sections= 1
Upstream XS Weight=0
Main XS Weight=1
Downstream XS Weight=0
Number of DS XS's Weighted with US Boundary= 1
Upstream Boundary Weight= 1
Weight of XSs Associated with US Boundary= 0
Number of US XS's Weighted with DS Boundary= 1
Downstream Boundary Weight= 0.5
Weight of XSs Associated with DS Boundary= 0.5
Percentile Method= 0
Sediment Output Level= 3
Mass or Volume Output= 0
Output Increment Type= 1
Profile and TS Output Increment= 1
Transport Output Increment 1
XS Output Flag= 0
XS Output Increment= 10
Read HDF5 Sediment Hotstart= 0
Sediment Hotstart Type= 0
Write Gradation File= 0
Read Gradation Hotstart= 0
Write HDF5 File= 1
Write Binary Output= 1
Write DSS Sediment File= 0
DSS Sediment Output Type= 1
SV Curve= 0
Specific Gage Flag= 0
Subcell Erosion Methods= 0
Subcell Deposition Methods= 0
Advection Scheme= 1
Matrix Solver= 0
Implicit Weighting Factor= 1
Maximum Outer Loop Convergence Iterations= 5
Convergence Maximum Absolute= 0.001
Convergence RMSE= 0.0001
Grain Fractions Max Abs Error= 0.001
Max Subgrid Regions= 1
Max Subgrid Length Scale= 3.402823E+38
Initial Layer Thickness= 3.402823E+38
Min Layer Thickness= 3.402823E+38
Max Layer Thickness= 3.402823E+38
Number of Layers= 5

--- BIRCHFK.f01 (steady flow) ---

Flow Title=Flow
Program Version=6.20
Number of Profiles= 1
Profile Names=P100yr
River Rch & RM=BIRCHFK,Main            ,29607
     406
River Rch & RM=BIRCHFK,Main            ,26536
     454
River Rch & RM=BIRCHFK,Main            ,25301
     507
River Rch & RM=BIRCHFK,Main            ,23528
     568
River Rch & RM=BIRCHFK,Main            ,19297
     723
River Rch & RM=BIRCHFK,Main            ,18510
     804
River Rch & RM=BIRCHFK,Main            ,16764
     894
River Rch & RM=BIRCHFK,Main            ,12052
    1570
River Rch & RM=BIRCHFK,Main            ,7191
    2050
River Rch & RM=BIRCHFK,Main            ,871
    3180
River Rch & RM=BIRCHFK,Main            ,0
    4040
Boundary for River Rch & Prof#=BIRCHFK,Main            , 1
Up Type= 0
Dn Type= 1
Dn Known WS=2309.7
DSS Import GetInterval= 0
DSS Import GetPeak= 0
DSS Import FillOption= 0

--- BIRCHFK.g01 (geometry) ---

Geom Title=Geometry
Program Version=6.20

River Reach=BIRCHFK         ,Main
Reach XY= 30
2226806.97357365 618511.643255832227064.76900001619673.181999996
      2227950.88621192.6260000172228804.48299998621574.006000012
2228977.22600003622101.3500000092229807.37600002622935.156000003
2230152.75463676623695.7266625912230274.91500001625149.288000003
2229557.02500004625822.0800000132229159.20900005626526.196999997
2229536.46500002627261.5139999992229672.03479454628133.156470329
     2230696.215628535.2412394882231288.58170466 629463.37265113
     2232475.324630114.6509999932233105.30600002630140.202000007
2233936.53400004630835.8530000152234325.61399999632325.230000004
2233995.38100003633052.147000015 2234449.4924466633752.678276718
2234281.45200001634262.1000000092234390.32200003635106.490999997
2235269.71600002 635174.157000022235890.51800004635841.341999993
2237056.62300003636267.7530000062237470.00700001636641.560000002
2238244.04799998636516.6170000142238722.08660467 636856.81219767
2239085.36000001636763.1630000032240525.49747127637094.041837811

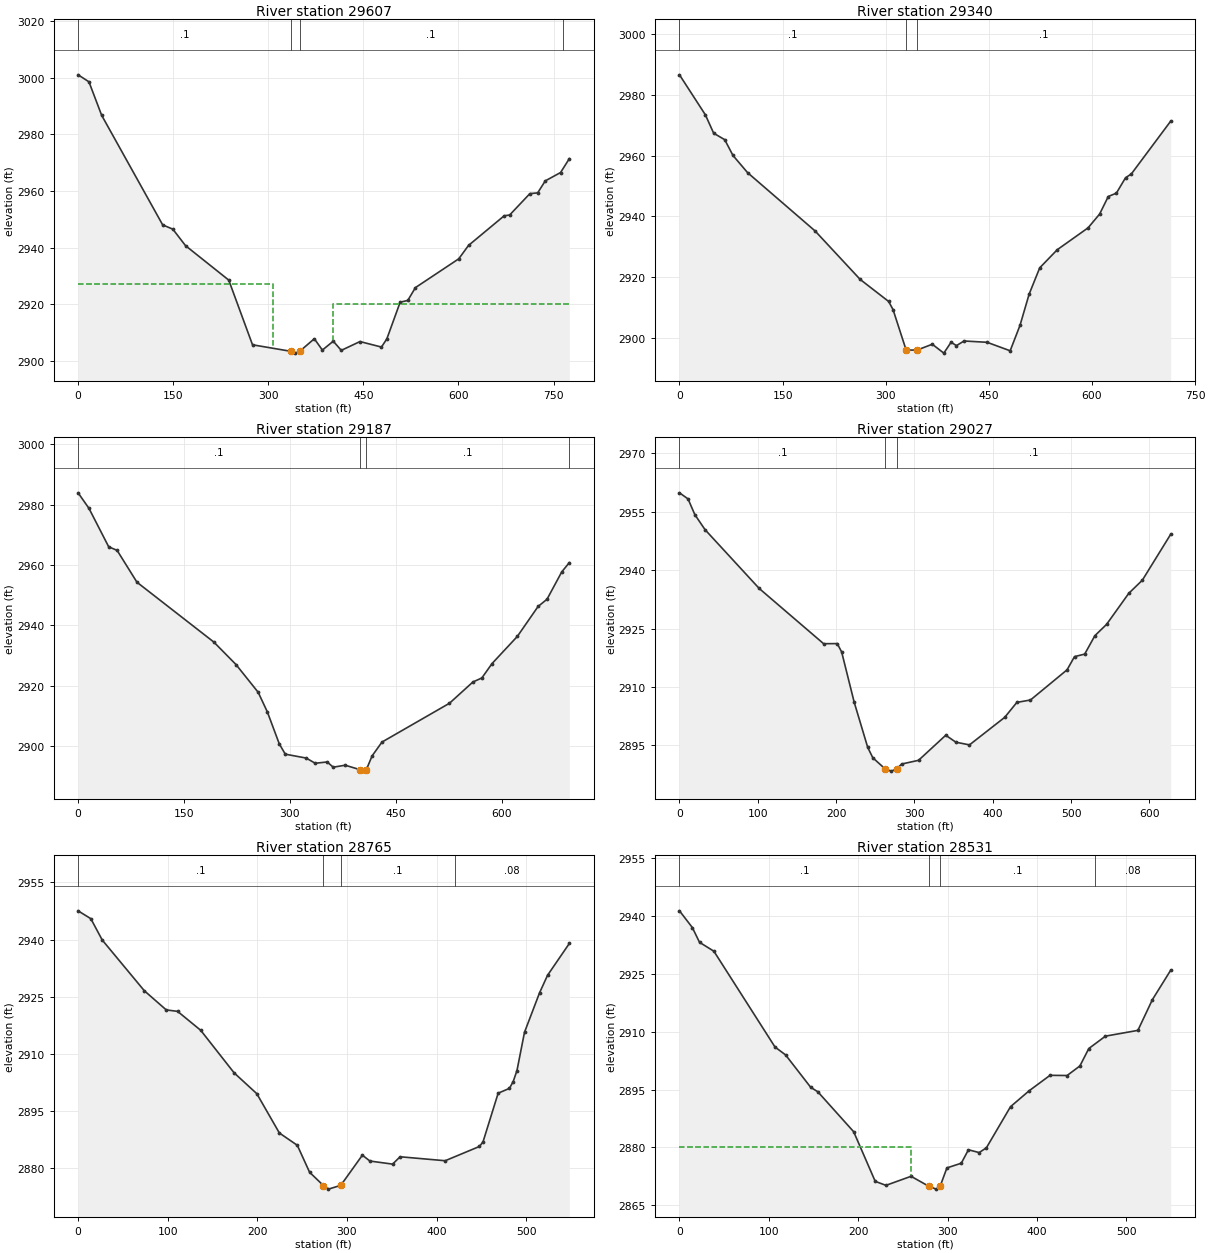
Type RM Length L Ch R = 1 ,29607   ,265.5,266.6,265.9
XS GIS Cut Line= 4
2226475.10082731618573.0762748512226724.10053815618555.983446034
2226964.67922446 618471.73755299     2227233.912618447.357074798
#Sta/Elev= 30
       0 3000.99    17.1 2998.53    37.2 2986.69   133.4 2948.07   149.4 2946.56
   169.5 2940.73   237.6  2928.6   275.1 2905.78   336.4 2903.45   342.9 2902.84
   349.5 2903.48   372.6 2907.91   385.3 2903.92   402.5 2907.05   415.1 2903.81
   444.6 2906.92   478.5 2904.98     487 2907.87     508 2920.81     520 2921.42
   532.1 2925.95   600.4  2936.1   615.9 2940.84   672.1 2951.28   680.7 2951.55
   712.6 2959.09   724.9 2959.36   736.9 2963.59     761 2966.53   774.8 2971.42
#Mann= 4 ,-1,0
       0      .1       0   336.4    .045       0   349.5      .1       0
  764.49     .08       0
#XS Ineff= 2 , 0
          307.87  2927.1   402.6         2920.07
Permanent Ineff=
       F       F
Bank Sta=336.4,349.5
XS Rating Curve= 0 ,0
Exp/Cntr=0.3,0.1

Type RM Length L Ch R = 1 ,29340   ,151,153.5,154.6
XS GIS Cut Line= 3
2226534.59226488618827.8445399342226787.87962883618807.782174473
2227226.74387331618668.599514083
#Sta/Elev= 30
       0 2986.53    37.7 2973.37    49.7 2967.35    65.8 2965.22    77.8 2960.04
      99  2954.4   197.3 2935.22   262.8 2919.31   304.2 2912.07   310.6 2909.41
   329.7 2896.09   345.6  2896.1   367.7 2898.01   384.5 2895.09     395 2898.66
   402.9 2897.56   413.9 2899.08   447.4 2898.65     481 2895.86   495.3 2904.21
   508.6 2914.48     524 2923.12   549.5 2929.07   594.3 2936.25   611.1 2940.78
   623.7 2946.55   635.5 2947.66   648.8 2952.71   657.2 2953.95   714.5 2971.31
#Mann= 3 ,-1,0
       0      .1       0   329.7    .045       0   345.6      .1       0
Bank Sta=329.7,345.6
XS Rating Curve= 0 ,0
Exp/Cntr(USF)=0,0
Exp/Cntr=0.3,0.1

Type RM Length L Ch R = 1 ,29187   ,164.7,159.7,151.7
XS GIS Cut Line= 4
2226544.96077569618878.3251160262226806.92009711618861.321007399
2226972.53993959618919.7037447912227218.30391649618841.962078627
#Sta/Elev= 30
       0 2983.96    15.4  2978.8    43.3 2966.07    55.3 2964.85    83.4 2954.29
   192.3 2934.44   223.7 2926.98   255.1 2917.78   268.1 2911.27     285 2900.67
   293.5 2897.24   323.2 2895.94   335.9 2894.22   352.9 2894.65   361.4 2892.92
   378.4 2893.57   399.6 2892.08   403.8 2891.61  408.362892.082   416.5 2896.66
   430.5 2901.25   526.1 2914.13   559.4  2921.2     572 2922.53   586.5 2927.32
   622.3 2936.32   651.7 2946.26   664.3 2948.64   685.2 2957.73   695.9 2960.79
#Mann= 4 ,-1,0
       0      .1       0   399.6    .045       0  408.36      .1       0
  695.89     .08       0
Bank Sta=399.6,408.36
XS Rating Curve= 0 ,0
Exp/Cntr(USF)=0,0
Exp/Cntr=0.3,0.1

Type RM Length L Ch R = 1 ,29027   ,261.4,262.2,263.1
XS GIS Cut Line= 2
2226622.08173286619129.3994473922227201.61576056 618889.90746749
#Sta/Elev= 30
       0 2959.88    10.9 2958.32    19.6 2954.28    32.6 2950.42   101.8  2935.3
     184 2921.11   201.4 2921.14     207 2919.01     223  2906.1   240.3 2894.47
   246.8  2891.8   262.4 2888.97   270.6 2888.37   277.4 2888.98   283.6 2890.19
   305.2 2891.15   339.9 2897.59   352.8 2895.81   370.2 2895.11   415.2 2902.19
   430.7 2906.03   448.1 2906.65   494.8  2914.4   504.3 2917.79   517.3 2918.44
   530.3 2923.17   545.2 2926.07   573.6 2934.06   590.9 2937.43   627.1 2949.23
#Mann= 3 ,-1,0
       0      .1       0   262.4    .045       0   277.4      .1       0
Bank Sta=262.4,277.4
XS Rating Curve= 0 ,0
Exp/Cntr(USF)=0,0
Exp/Cntr=0.3,0.1

Type RM Length L Ch R = 1 ,28765   ,231.9,233.9,234.8
XS GIS Cut Line= 2
2226722.63180076619324.1009425042227243.66397078619154.079918604
#Sta/Elev= 30
       0 2947.53    14.2 2945.47    26.9 2939.88    73.9 2926.56    98.4 2921.53
     111 2921.16   136.8 2916.19   174.1 2905.02   199.4 2899.56   224.6 2889.24
   244.6 2886.02   258.3 2878.95  273.752875.461   279.3 2874.52   293.1 2875.51
   317.2 2883.43   325.6 2881.89   350.9 2881.08   359.3 2883.01   409.6 2881.97
   447.8 2885.71   451.8 2886.91   468.7 2899.69   481.3 2900.95   485.5 2902.75
   489.7 2905.63   498.1 2915.67   514.9 2926.02   523.8 2930.61   548.1 2938.96
#Mann= 4 ,-1,0
       0      .1       0  273.75    .045       0   293.1      .1       0
     420     .08       0
Bank Sta=273.75,293.1
XS Rating Curve= 0 ,0
Exp/Cntr(USF)=0,0
Exp/Cntr=0.3,0.1

Type RM Length L Ch R = 1 ,28531   ,167.9,166.6,163.9
XS GIS Cut Line= 3
2226773.82092623 619477.668318932227117.51934014619451.159664666
2227289.36854709619339.640498452
#Sta/Elev= 30
       0  2941.4    14.4 2937.05    22.4 2933.23    38.5 2930.91   106.9 2906.03
   118.7 2903.99   146.8 2895.58   154.8 2894.41   194.9 2884.04     219 2871.16
     231 2870.12   259.1 2872.47   279.2 2869.85   287.2 2869.14  291.632869.884
   299.2 2874.65   315.3 2875.87   323.3 2879.36   335.3 2878.63   343.4 2879.87
   370.4 2890.55   391.4 2894.71   414.6 2898.69   433.7 2898.64     448 2901.12
     458 2905.65   476.6 2908.86   512.9 2910.36   529.1 2918.33   549.6 2925.98
#Mann= 4 ,-1,0
       0      .1       0   279.2    .045       0  291.63      .1       0
  464.72     .08       0
#XS Ineff= 2 , 0
          259.21 2880.11
Permanent Ineff=
       F       F
Bank Sta=279.2,291.63
XS Rating Curve= 0 ,0
Exp/Cntr(USF)=0,0
Exp/Cntr=0.3,0.1

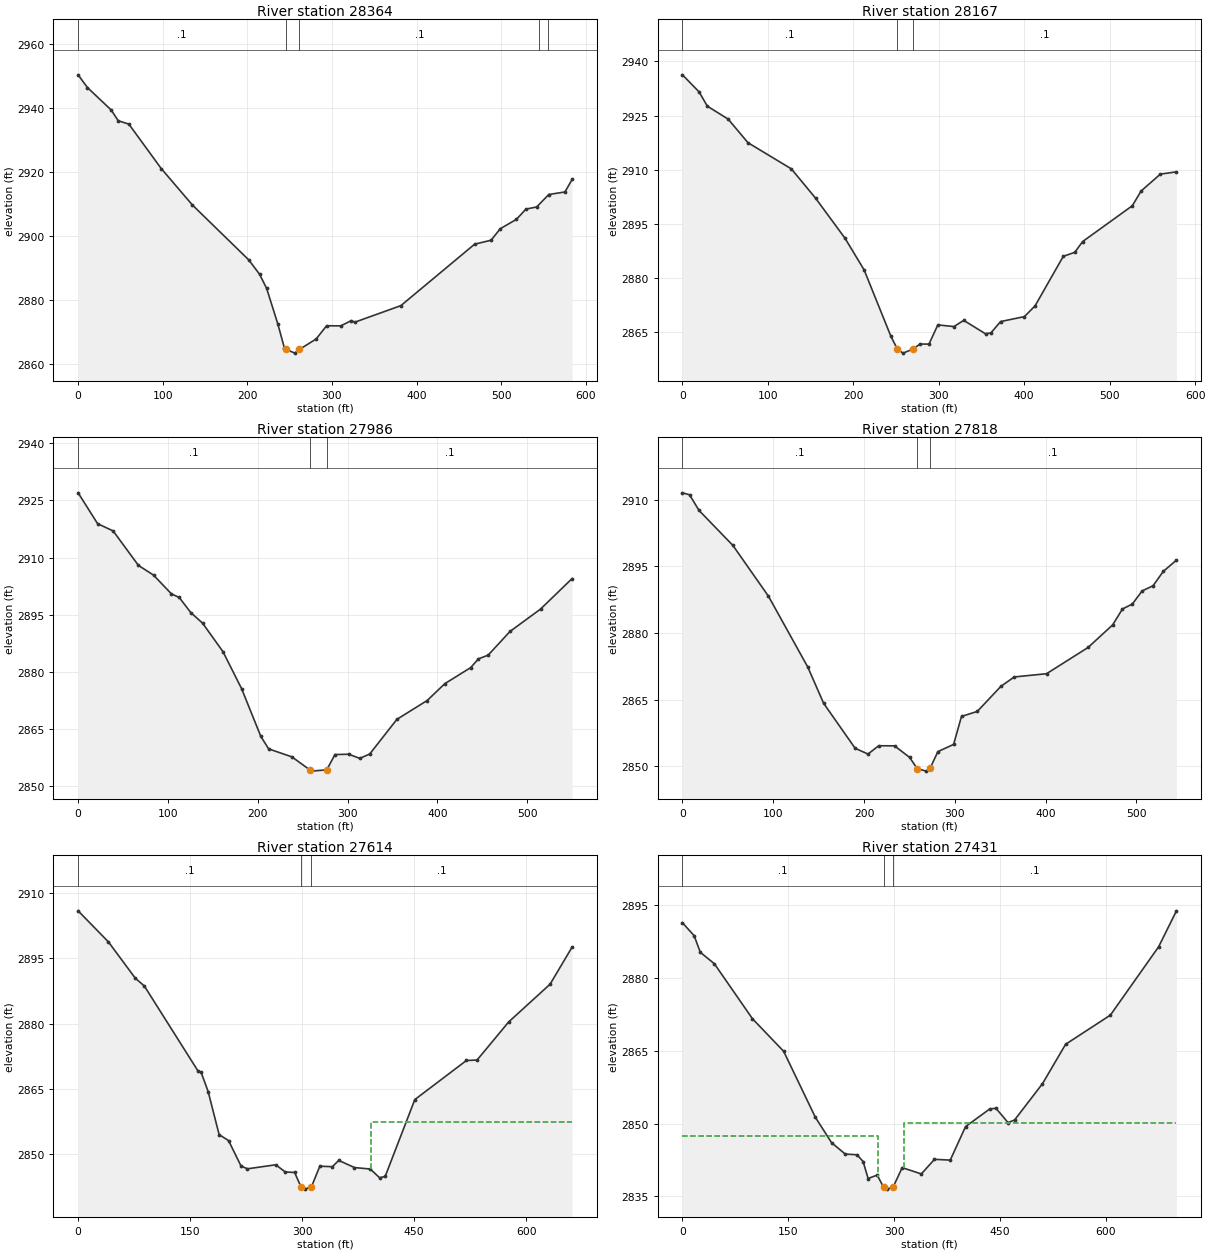
Type RM Length L Ch R = 1 ,28364   ,200,197,193.3
XS GIS Cut Line= 3
2226806.72822118619693.3939191472227185.16211309 619580.04656988
2227343.29994715619476.754227403
#Sta/Elev= 30
       0 2950.27      11  2946.3    39.1 2939.29    47.4 2935.94      60 2934.88
    98.3 2920.99   135.1 2909.63   201.9 2892.44   214.5    2888   222.8 2883.61
   235.9 2872.63   243.7 2865.11   245.5 2864.59   256.2 2863.39   261.6 2864.55
   281.3  2867.8   293.7 2871.93   310.5  2871.9   322.7 2873.53   327.2 2873.06
   381.5 2878.22   468.7 2897.41   488.1 2898.63     499 2902.23   518.1 2905.16
   529.3 2908.35     542 2909.02   556.3 2912.91   575.4  2913.7   583.9 2917.61
#Mann= 5 ,-1,0
       0      .1       0   245.5    .045       0   261.6      .1       0
  545.04     .08       0  555.04      .1       0
Bank Sta=245.5,261.6
XS Rating Curve= 0 ,0
Exp/Cntr(USF)=0,0
Exp/Cntr=0.3,0.1

Type RM Length L Ch R = 1 ,28167   ,178.6,181.5,184.1
XS GIS Cut Line= 3
2226941.75870858619958.1587015212227101.80448805619825.461352526
2227388.20652526619590.719922053
#Sta/Elev= 30
       0 2936.27    19.5 2931.54    29.1  2927.6    53.5 2924.01    76.7 2917.48
   127.4 2910.25   155.8 2902.14   190.2 2891.06   212.6  2882.3   243.9 2863.95
   251.5 2860.39   258.1 2859.25   269.5 2860.33   278.2 2861.77   288.5 2861.74
   298.9 2867.06   317.8  2866.6   329.2 2868.32   354.7  2864.6     361 2864.84
   372.4 2867.99   400.2 2869.35   412.7 2872.33   445.7 2886.03   459.2 2887.15
   468.4 2890.13   526.5 2900.03   536.8 2904.11   559.4  2908.8   578.2 2909.41
#Mann= 3 ,-1,0
       0      .1       0   251.5    .045       0   269.5      .1       0
Bank Sta=251.5,269.5
XS Rating Curve= 0 ,0
Exp/Cntr=0.3,0.1

Type RM Length L Ch R = 1 ,27986   ,167.7,167.4,167.2
XS GIS Cut Line= 3
2227004.17199087620038.9205161062227335.07312341619901.806787154
2227493.21095747619793.029895519
#Sta/Elev= 30
       0 2927.01    21.7 2918.91      39    2917    67.2 2907.94      84 2905.39
   103.9 2900.47   112.6 2899.52   125.6 2895.52   138.6 2892.78   161.3 2885.29
     182 2875.59   203.5 2863.01   212.2 2859.75   238.1 2857.65     2582854.246
   259.8 2853.91   276.9 2854.25     286 2858.26   301.3 2858.35   313.6 2857.26
   324.7  2858.4     355 2867.52   388.7 2872.46   408.3 2876.88   437.2 2881.11
   445.7 2883.39   456.6 2884.38   480.9 2890.59   514.9 2896.47   550.1  2904.5
#Mann= 3 ,-1,0
       0      .1       0     258    .045       0   276.9      .1       0
Bank Sta=258,276.9
XS Rating Curve= 0 ,0
Exp/Cntr(USF)=0,0
Exp/Cntr=0.3,0.1

Type RM Length L Ch R = 1 ,27818   ,203.8,204.5,205
XS GIS Cut Line= 3
2227080.95567909620189.7456179532227410.02862857620050.803705948
2227548.05644905619924.659075313
#Sta/Elev= 30
       0 2911.52     7.8 2911.08    18.2 2907.57    55.6 2899.68    94.7 2888.27
   138.1  2872.3   155.5 2864.17   190.2 2854.05   204.4 2852.74   216.2 2854.61
   233.6 2854.59   250.2    2852   258.5 2849.49   268.4  2848.9   272.7  2849.5
   281.4 2853.29   298.7 2854.91   307.4 2861.21   324.8 2862.33   350.8 2867.98
   365.5 2870.09   401.1 2870.82   446.8 2876.72   473.9  2881.8   484.7 2885.38
   495.6  2886.5   506.4 2889.45   518.4 2890.61   529.7 2893.85   544.2 2896.37
#Mann= 3 ,-1,0
       0      .1       0   258.5    .045       0   272.7      .1       0
Bank Sta=258.5,272.7
XS Rating Curve= 0 ,0
Exp/Cntr(USF)=0,0
Exp/Cntr=0.3,0.1

Type RM Length L Ch R = 1 ,27614   ,185.3,182.9,180.6
XS GIS Cut Line= 4
2227107.62563064620305.0474608912227293.94910158620311.008562738
2227518.80552021620236.3642857962227689.32180663620070.178867735
#Sta/Elev= 30
       0 2905.94    40.6 2898.79    76.6 2890.44    88.6 2888.67   160.6 2869.09
   164.6 2868.84   174.1 2864.38   188.8 2854.48   201.4 2853.12   218.1 2847.27
   226.7 2846.62   264.6 2847.55   277.3  2845.9   289.9 2845.78   298.3 2842.49
   303.5 2841.95  312.452842.511   323.6 2847.22   340.5 2847.11   348.9 2848.56
     370 2846.91   391.1 2846.57   403.7 2844.56   411.1 2844.87   450.8 2862.54
   519.9 2871.53   534.1 2871.63   576.5  2880.4   631.9 2889.07   661.4 2897.61
#Mann= 3 ,-1,0
       0      .1       0   298.3    .045       0  312.45      .1       0
#XS Ineff= 2 , 0
                           391.7         2857.38
Permanent Ineff=
       F       F
Bank Sta=298.3,312.45
XS Rating Curve= 0 ,0
Exp/Cntr=0.3,0.1

Type RM Length L Ch R = 1 ,27431   ,242.8,241.1,239.1
XS GIS Cut Line= 4
2227354.26904546620693.4100489692227395.40316415620504.193103016
2227548.97054058620383.5330215382227728.13247974620128.501485688
#Sta/Elev= 30
       0 2891.38    16.6  2888.7    25.3 2885.29    45.3 2882.92    99.3 2871.59
   143.5 2864.89   188.5 2851.28   211.5 2846.05   230.9  2843.7   247.6 2843.56
   256.2 2842.17   263.3 2838.67   276.2 2839.38  285.212836.868   290.3 2836.48
   298.9 2836.93   311.6 2840.91   338.8 2839.61   357.4 2842.62   379.8 2842.46
   401.5 2849.37     436 2853.02   444.6 2853.14   461.8 2850.18   471.1 2850.74
   510.6 2858.21   543.4 2866.33   606.9 2872.34   675.3 2886.42   700.6 2893.83
#Mann= 3 ,-1,0
       0      .1       0  285.21    .045       0   298.9      .1       0
#XS Ineff= 2 , 0
          277.83 2847.38  313.65         2850.03
Permanent Ineff=
       F       F
Bank Sta=285.21,298.9
XS Rating Curve= 0 ,0
Exp/Cntr(USF)=0,0
Exp/Cntr=0.3,0.1

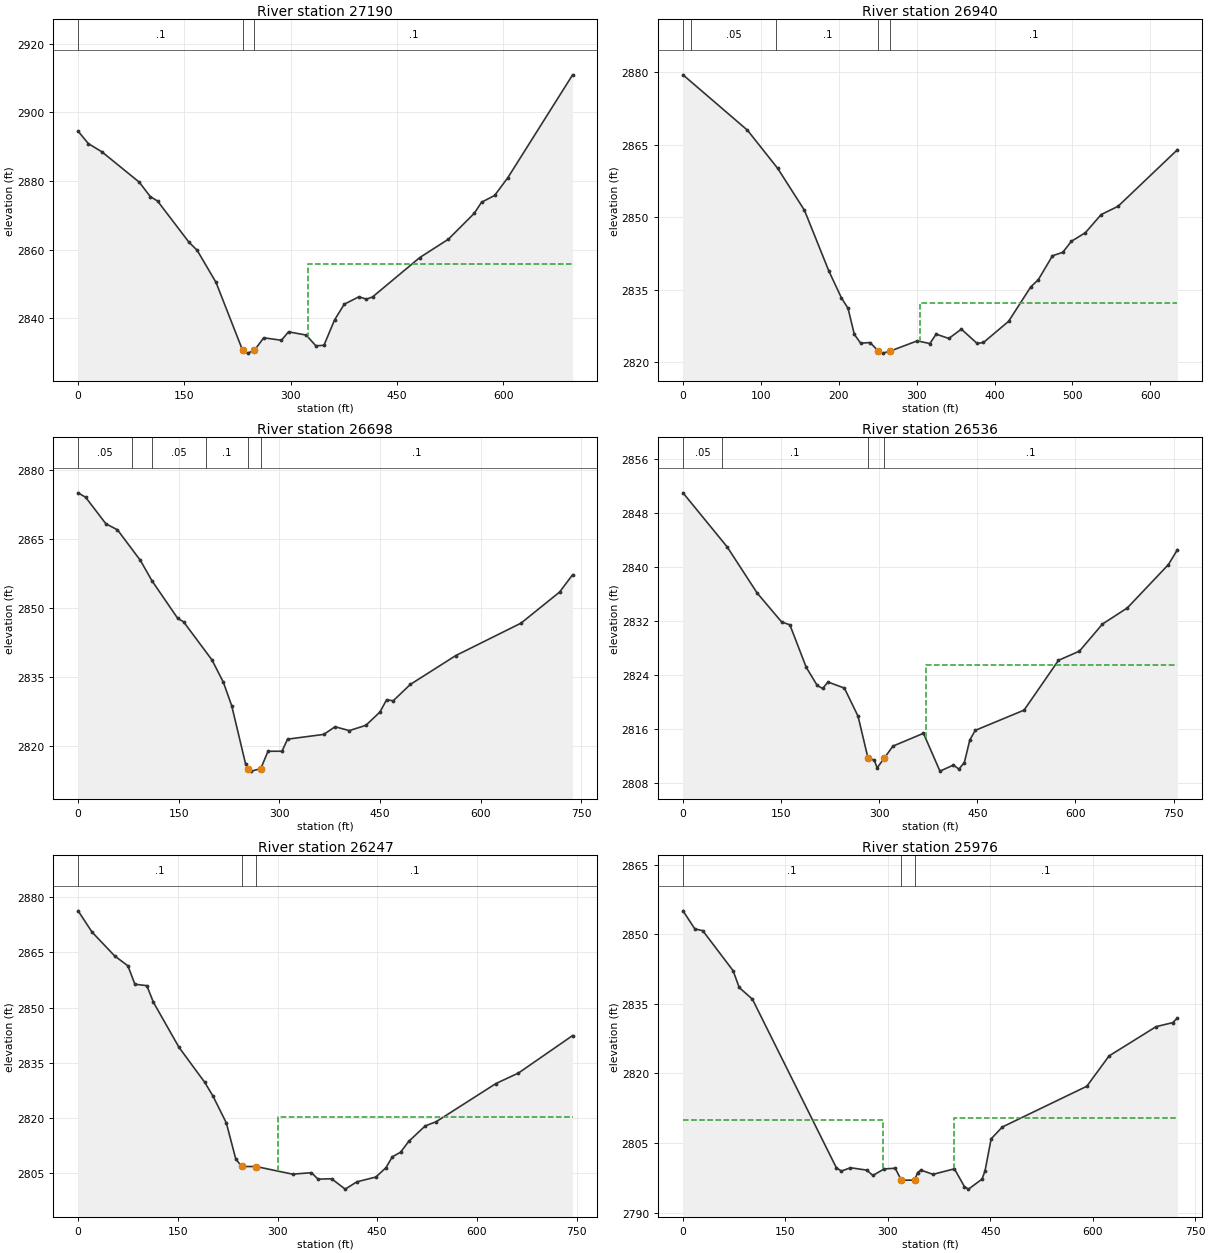
Type RM Length L Ch R = 1 ,27190   ,245.2,250.2,256.5
XS GIS Cut Line= 3
2227473.15006111620754.2754913092227640.41821347620618.416888104
2227929.10089489620232.045711841
#Sta/Elev= 30
       0 2894.51    14.4 2890.89    33.5  2888.5    86.3 2879.63   101.8 2875.44
   112.1 2874.14   156.5  2862.1   167.9 2859.79   194.6  2850.4     232 2830.65
   239.1 2829.78   248.5 2830.56   261.9 2834.25   286.9 2833.53   296.9 2835.99
   321.9 2835.04   335.4 2831.92   346.9 2832.06   361.8 2839.44   375.5 2844.04
   396.2 2846.22   406.8 2845.51   415.6 2846.19     482 2857.64   522.5 2863.01
   559.1 2870.58   569.3  2873.8   587.7 2875.76   606.5 2880.99   697.8 2910.95
#Mann= 3 ,-1,0
       0      .1       0     232    .045       0   248.5      .1       0
#XS Ineff= 2 , 0
                          324.98         2855.69
Permanent Ineff=
       F       F
Bank Sta=232,248.5
XS Rating Curve= 0 ,0
Exp/Cntr=0.3,0.1

Type RM Length L Ch R = 1 ,26940   ,242.9,241.8,240.3
XS GIS Cut Line= 4
2227599.24557452620839.6646931842227793.94706964620761.966913445
2228028.86859191620727.2314354442228169.63868696620602.914987861
#Sta/Elev= 30
       0 2879.45    82.8 2867.98   121.6 2860.09     156  2851.4   187.3 2838.84
   203.4 2833.29   211.9 2831.12     220 2825.73   228.1 2823.91   240.2 2824.04
     251 2822.26   256.4 2821.85   265.7 2822.25   300.8 2824.39     317 2823.83
     325 2825.78   341.3 2824.89   357.4 2826.81   377.7 2823.85   385.8 2824.05
   418.1 2828.44   446.4 2835.53   456.3 2837.07   474.4    2842   487.7 2842.72
   498.6 2844.99   516.7 2846.78   536.9 2850.53   558.6 2852.24   634.9 2863.96
#Mann= 5 ,-1,0
       0      .1       0      10     .05       0     120      .1       0
     251    .045       0   265.7      .1       0
#XS Ineff= 2 , 0
                          304.71         2832.15
Permanent Ineff=
       F       F
Bank Sta=251,265.7
XS Rating Curve= 0 ,0
Exp/Cntr(USF)=0,0
Exp/Cntr=0.3,0.1

Type RM Length L Ch R = 1 ,26698   ,162.2,162.2,162.4
XS GIS Cut Line= 4
 2227633.4662849620941.4481827812227814.05708322621010.599808611
2228001.37878653620956.6923693642228221.27574226620686.131159153
#Sta/Elev= 30
       0 2874.95    11.2 2873.98    41.4 2868.22    58.6 2866.92    92.8 2860.27
     110 2855.86   148.5 2847.67   157.1 2846.95   199.5 2838.65   216.4 2833.83
   228.9  2828.7   249.7    2816   252.8 2815.07     258 2814.51   272.22815.054
     283 2818.83   303.8 2818.83   312.1 2821.45   366.2 2822.49   382.9 2824.15
   404.2 2823.31   428.9 2824.46   449.8 2827.34   459.8 2830.02   469.6 2829.79
   495.2 2833.35   562.9 2839.61   660.1 2846.65   717.6  2853.4     737 2857.17
#Mann= 6 ,-1,0
       0     .05       0      80      .1       0     110     .05       0
     190      .1       0   252.8    .045       0   272.2      .1       0
Bank Sta=252.8,272.2
XS Rating Curve= 0 ,0
Exp/Cntr=0.3,0.1

Type RM Length L Ch R = 1 ,26536   ,294.3,289,279.2
XS GIS Cut Line= 3
2227651.34879153621227.2395003552228098.33954791621096.524412087
2228274.75921249620866.173347448
#Sta/Elev= 30
       0 2850.99    67.5 2842.97   113.4 2836.12   150.7 2831.84   163.4  2831.4
   188.4  2825.1   205.1 2822.42   213.4 2821.96   221.7 2822.92   246.7 2822.02
   267.6 2817.85   282.9  2811.6   292.4 2811.35   296.8 2810.18  307.462811.603
   320.9 2813.41   367.6 2815.31   392.8  2809.7   413.4  2810.6   421.8    2810
   430.1 2810.98   438.5 2814.34   446.8 2815.75   521.4 2818.75     574 2826.14
     606  2827.5   641.2 2831.52   679.2 2833.91     742 2840.34   755.9 2842.56
#Mann= 4 ,-1,0
       0     .05       0      60      .1       0   282.9    .045       0
  307.46      .1       0
#XS Ineff= 2 , 0
                          370.83         2825.45
Permanent Ineff=
       F       F
Bank Sta=282.9,307.46
XS Rating Curve= 0 ,0
Exp/Cntr(USF)=0,0
Exp/Cntr=0.3,0.1

Type RM Length L Ch R = 1 ,26247   ,271.5,270.4,266.4
XS GIS Cut Line= 3
2227969.87684383621548.1454369912228262.11990847621179.338125204
2228329.45190851 620914.22399683
#Sta/Elev= 30
       0 2876.24    20.8  2870.5      55    2864    74.9 2861.32    85.4 2856.33
   103.4 2855.94   113.2 2851.46   151.8 2839.21   190.5 2829.72   202.8 2826.03
     223 2818.71   237.2 2808.93  246.052806.888   267.8 2806.88   322.6 2804.81
   351.1 2805.21     361 2803.46   381.4 2803.56   401.9 2800.75   419.5 2802.74
   447.9 2804.02   463.1 2806.54   472.8 2809.52   485.2 2810.77   497.5  2813.7
   522.3  2817.9   538.8 2819.04   628.7 2829.39   662.6 2832.24   744.1 2842.41
#Mann= 3 ,-1,0
       0      .1       0  246.05    .045       0   267.8      .1       0
#XS Ineff= 2 , 0
                          300.94         2820.41
Permanent Ineff=
       F       F
Bank Sta=246.05,267.8
XS Rating Curve= 0 ,0
Exp/Cntr=0.3,0.1

Type RM Length L Ch R = 1 ,25976   ,332.6,335.4,335
XS GIS Cut Line= 4
2228183.67449481621673.1115541112228332.43982672 621524.36820288
2228451.49525246621287.8697137062228492.77630893621042.294032571
#Sta/Elev= 30
       0 2855.06    17.3 2851.17      29 2850.77    73.4 2842.15    82.3 2838.53
   101.7    2836   224.5 2799.69   231.9 2798.94   245.3 2799.66   269.1 2799.15
   278.1 2797.99   294.5  2799.4   310.8 2799.56   319.8 2796.97   339.3 2796.99
   343.6 2798.63   348.3 2799.15   366.2 2798.24   397.5 2799.43   412.1 2795.61
   418.1 2795.05   437.9  2797.2   442.3 2798.96   451.3  2805.9   467.8 2808.46
   591.4 2817.23     624 2823.77   692.8 2830.08   717.2 2830.95   724.2 2831.96
#Mann= 3 ,-1,0
       0      .1       0   319.8    .045       0   339.3      .1       0
#XS Ineff= 2 , 0
          292.85 2810.03   397.4         2810.28
Permanent Ineff=
       F       F
Bank Sta=319.8,339.3
XS Rating Curve= 0 ,0
Exp/Cntr(USF)=0,0
Exp/Cntr=0.3,0.1

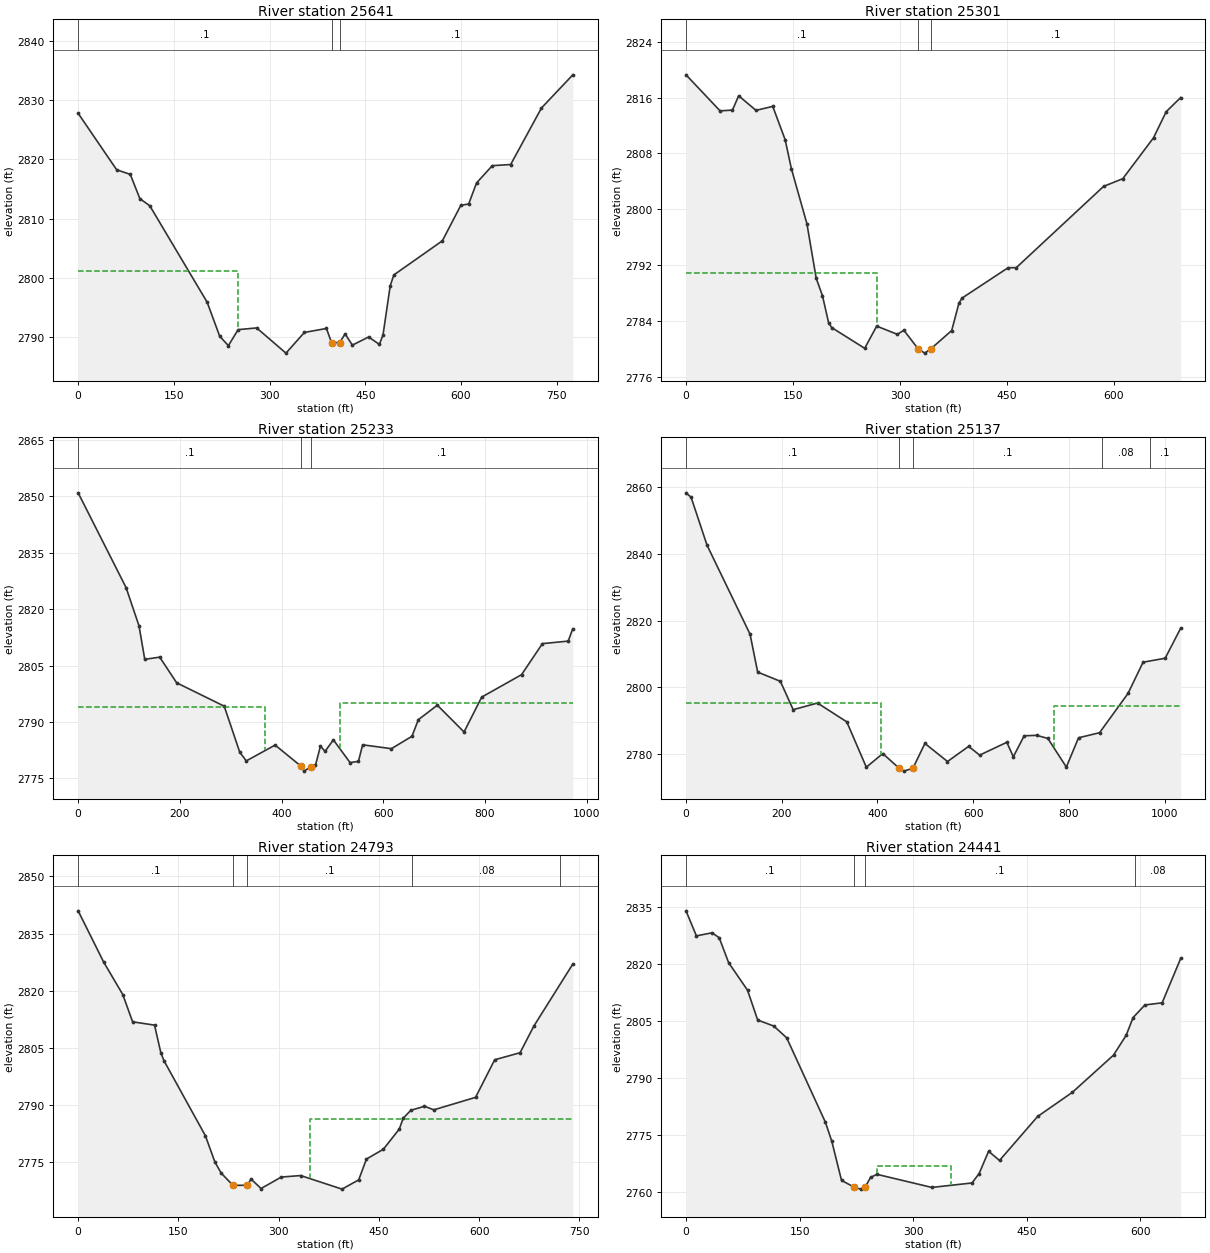
Type RM Length L Ch R = 1 ,25641   ,335.7,339.9,342
XS GIS Cut Line= 3
2228394.31547583621810.8877829082228739.62671754621452.023879594
2228804.71529096621182.529927032
#Sta/Elev= 30
       0 2827.75    60.4 2818.22    81.7 2817.45    96.7 2813.36   112.3 2812.15
   202.2 2795.89   221.9 2790.14   235.5 2788.56   250.7 2791.26   279.8 2791.55
   325.7  2787.3   354.6 2790.79   389.2 2791.46  397.092789.077   409.9 2789.09
   418.4 2790.54   429.8 2788.65   455.2 2790.02   472.1 2788.78   477.8 2790.35
   489.1 2798.65   494.8 2800.49   570.9 2806.25   599.7 2812.22   612.1 2812.46
   624.4    2816   649.1 2818.92   677.9 2819.11   726.2 2828.65   775.3 2834.24
#Mann= 3 ,-1,0
       0      .1       0  397.09    .045       0   409.9      .1       0
#XS Ineff= 2 , 0
          250.69  2801.1
Permanent Ineff=
       F       F
Bank Sta=397.09,409.9
XS Rating Curve= 0 ,0
Exp/Cntr=0.3,0.1

Type RM Length L Ch R = 1 ,25301   ,68.8,68.3,67.9
BEGIN DESCRIPTION:
Structure XS 4
END DESCRIPTION:
XS GIS Cut Line= 3
2228536.32517076621894.1181085672228914.37536992621732.741456385
 2229028.3546837621474.313111282
#Sta/Elev= 30
       0 2819.25    47.7 2814.09    65.1  2814.2    73.8 2816.25    98.1 2814.16
   121.6 2814.73     139 2809.95   147.7 2805.81   169.5 2797.92   182.5 2790.11
   191.2 2787.64   199.9 2783.75   204.2 2783.05   250.5 2780.08   267.3 2783.26
   296.3 2782.08   305.4 2782.67  325.422780.002   334.7 2779.39   343.4 2780.02
   372.5 2782.63   382.6 2786.54   386.9 2787.27   451.5 2791.62     463 2791.63
   585.4 2803.27   612.3 2804.37   655.4 2810.23   673.2 2813.97   693.5    2816
#Mann= 3 ,-1,0
       0      .1       0  325.42    .045       0   343.4      .1       0
#XS Ineff= 2 , 0
          268.38 2790.86
Permanent Ineff=
       F       F
Bank Sta=325.42,343.4
XS Rating Curve= 0 ,0
Exp/Cntr(USF)=0,0
Exp/Cntr=0.3,0.1

Type RM Length L Ch R = 1 ,25233   ,95.6,95.3,95.3
BEGIN DESCRIPTION:
Structure XS 3
END DESCRIPTION:
XS GIS Cut Line= 6
2228669.48912151622159.317502013  2228777.825895622065.651333264
 2228801.5245642621861.3913749082228994.49944199 621783.52431896
2229214.55851314621845.592262106 2229347.7224639621744.026536957
#Sta/Elev= 30
       0 2850.96    94.2 2825.78   119.7 2815.59     131 2806.68   160.4 2807.27
   193.8 2800.44   287.3 2794.23   317.9 2781.97   330.7 2779.68   387.4 2783.89
  438.222778.282   444.4 2776.96   457.8 2778.14   466.8 2778.52   476.6 2783.63
   485.6 2782.21     502 2785.27   534.8 2779.23   551.3 2779.55   559.5 2783.96
   616.1 2782.93   656.6 2786.23   669.1 2790.64   706.5 2794.49     759 2787.37
   793.7 2796.64   872.1 2802.61   913.1 2810.86   963.8 2811.53   972.9 2814.83
#Mann= 3 ,-1,0
       0      .1       0  438.22    .045       0   457.8      .1       0
#XS Ineff= 2 , 0
          368.23 2794.05  515.52         2795.14
Permanent Ineff=
       F       F
Bank Sta=438.22,457.8
XS Rating Curve= 0 ,0
Exp/Cntr(USF)=0,0
Exp/Cntr=0.3,0.1

Type RM Length L Ch R = 1 ,25137   ,342.8,344.2,340.5
BEGIN DESCRIPTION:
Structure XS 2
END DESCRIPTION:
XS GIS Cut Line= 6
2228730.99281063622234.9275418462228890.67670072622094.992542751
2228863.02825332621937.0014147412229046.97506665621881.704519937
 2229227.5363558621968.5996403432229409.22615301 621819.63657679
#Sta/Elev= 30
       0 2858.31    10.6 2856.98    43.9  2842.6   133.8 2815.91   149.7 2804.55
   197.1 2801.79   223.9 2793.28   274.7 2795.27   335.9 2789.62   376.7 2776.03
   411.1 2780.11   445.4 2775.71   455.5 2774.85  474.162775.727   499.1 2783.16
   546.3 2777.73   590.4 2782.27   613.5 2779.65   670.3  2783.5   683.8 2779.14
   706.5 2785.45   732.4 2785.58     756 2784.66   794.6 2776.07   820.1 2784.85
     864 2786.37   923.5 2798.16   954.9 2807.51  1001.1 2808.71  1033.5 2817.71
#Mann= 5 ,-1,0
       0      .1       0   445.4    .045       0  474.16      .1       0
  868.56     .08       0  968.56      .1       0
#XS Ineff= 2 , 0
          408.09 2795.17  769.39         2794.48
Permanent Ineff=
       F       F
Bank Sta=445.4,474.16
XS Rating Curve= 0 ,0
Exp/Cntr(USF)=0,0
Exp/Cntr=0.3,0.1

Type RM Length L Ch R = 1 ,24793   ,350.2,352.5,352.2
BEGIN DESCRIPTION:
Structure XS 1
END DESCRIPTION:
XS GIS Cut Line= 3
2228868.10653958622317.3086300232229441.38863264621948.286495313
2229498.94254356621938.129922798
#Sta/Elev= 30
       0 2840.99    38.1 2827.57    66.8 2819.02    81.5 2811.87   114.3    2811
   123.8 2803.72   128.5 2801.64   190.4 2781.98   204.6 2775.09   214.1 2772.17
   231.7 2768.95  252.742768.992   258.9 2770.58   273.7 2768.13     304 2771.14
     333 2771.53   394.9 2767.97   419.8  2770.4   431.4 2775.86   456.8 2778.44
   480.6 2783.75   486.4 2786.59   497.9 2788.66   518.2  2789.7   532.3 2788.78
   594.7 2792.05   623.3 2801.91   661.3 2803.76   681.8 2810.72   740.2 2827.02
#Mann= 5 ,-1,0
       0      .1       0   231.7    .045       0  252.74      .1       0
     500     .08       0  721.78      .1       0
#XS Ineff= 2 , 0
                          347.15         2786.38
Permanent Ineff=
       F       F
Bank Sta=231.7,252.74
XS Rating Curve= 0 ,0
Exp/Cntr(USF)=0,0
Exp/Cntr=0.3,0.1

Type RM Length L Ch R = 1 ,24441   ,295,296.9,296
XS GIS Cut Line= 4
2229019.32661925 622476.42826609 2229418.8184715 622330.85072671
2229570.03855117622285.7104044212229628.72097014622247.341130476
#Sta/Elev= 30
       0 2834.09    13.7  2827.5    34.4 2828.31    43.8 2827.01    56.3 2820.43
    81.2 2813.21    94.6 2805.36   115.9 2803.77   132.9 2800.68     184 2778.48
   192.5 2773.43   205.3 2763.17   222.3 2761.35   230.8 2760.87  236.452761.361
   243.6 2763.96   252.1 2764.76   324.5 2761.32   377.6 2762.49     387 2764.98
   399.5 2770.83   413.9 2768.41   464.2 2779.98   510.1 2786.34   564.4 2796.12
   581.1 2801.34   590.3 2806.02   605.9 2809.33   628.6 2809.88   653.1 2821.56
#Mann= 4 ,-1,0
       0      .1       0   222.3    .045       0  236.45      .1       0
     593     .08       0
#XS Ineff= 1 ,-1
   252.1  349.752767.024
Permanent Ineff=
       F
Bank Sta=222.3,236.45
XS Rating Curve= 0 ,0
Exp/Cntr(USF)=0,0
Exp/Cntr=0.3,0.1

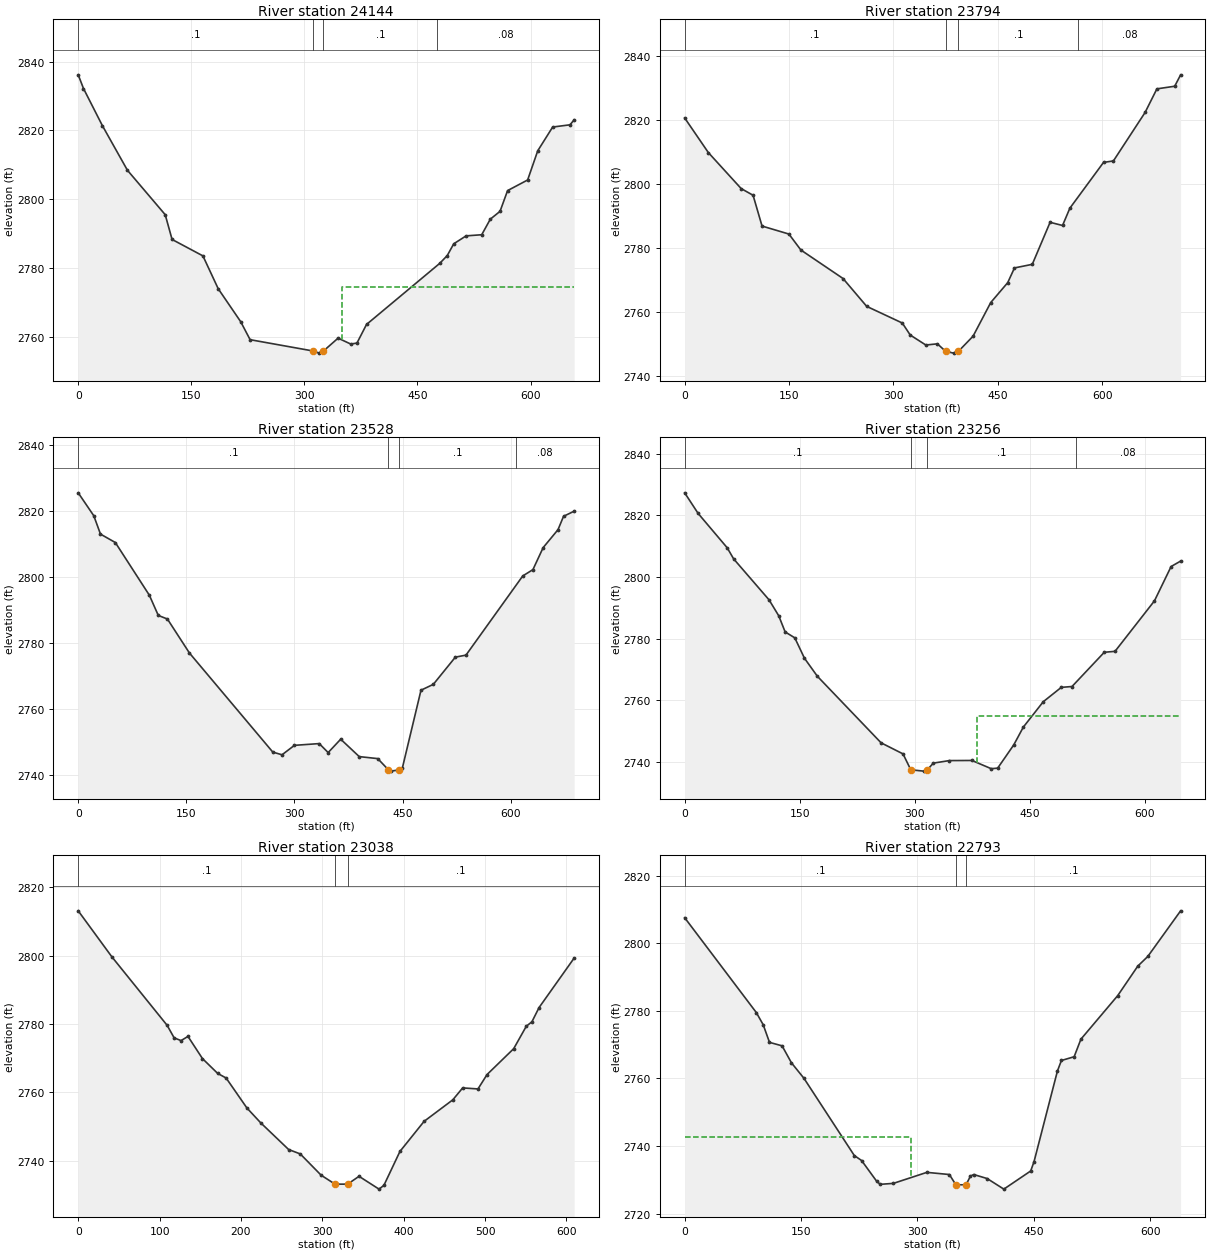
Type RM Length L Ch R = 1 ,24144   ,352.4,349.5,345.7
XS GIS Cut Line= 3
2229133.49432989622685.0897591892229513.87349955 622573.04656491
2229722.69233931 622416.10543509
#Sta/Elev= 30
       0 2836.16       7 2832.18      32  2821.4    65.3 2808.39   115.4 2795.47
   124.5 2788.27   165.4 2783.49   185.7 2773.93   215.5 2764.35     228 2759.11
   311.1 2755.84   319.7  2755.2   325.3 2755.82   344.7 2759.56   361.4 2757.85
   369.7 2758.12   382.4 2763.54   479.5 2781.31   489.5 2783.59   498.1 2787.01
   514.5 2789.31   535.2 2789.64   546.6 2794.17   559.5 2796.45   569.5 2802.48
   596.1 2805.57   609.5 2814.06   629.3 2820.97   652.3 2821.62   657.8 2823.07
#Mann= 4 ,-1,0
       0      .1       0   311.1    .045       0   325.3      .1       0
  476.54     .08       0
#XS Ineff= 2 , 0
                          349.75         2774.48
Permanent Ineff=
       F       F
Bank Sta=311.1,325.3
XS Rating Curve= 0 ,0
Exp/Cntr=0.3,0.1

Type RM Length L Ch R = 1 ,23794   ,263.4,266.7,269
XS GIS Cut Line= 4
2229292.49438765 622952.036445412229568.63561416622844.886040739
2229674.98980049622739.3706434222229843.19872696622532.248427485
#Sta/Elev= 30
       0 2820.58      34 2809.78    81.2 2798.54    98.3 2796.46   111.2 2786.85
   149.8 2784.36     167 2779.38   227.6 2770.49   261.6  2761.8   312.8  2756.6
   324.2 2752.85   346.6 2749.74   363.2 2750.11   375.3 2747.73   386.7 2747.21
   393.42747.758   414.5  2752.5   439.9 2762.99   464.3  2769.2     474 2773.79
   499.6 2774.91   525.2 2788.02   543.1 2787.03   553.6 2792.42     602 2806.71
   616.2 2807.17   661.7 2822.28   678.7 2829.65   704.3 2830.47   712.8 2834.03
#Mann= 4 ,-1,0
       0      .1       0   375.3    .045       0   393.4      .1       0
  566.02     .08       0
Bank Sta=375.3,393.4
XS Rating Curve= 0 ,0
Exp/Cntr=0.3,0.1

Type RM Length L Ch R = 1 ,23528   ,272.2,271.7,270.3
XS GIS Cut Line= 3
2229412.04742316623112.906810361 2229904.0769361622924.445964805
2230040.62641103622838.679352457
#Sta/Elev= 30
       0 2825.54    21.6  2818.6    30.9 2813.04    51.5 2810.49    98.7 2794.53
   111.1 2788.41   123.8 2787.31   154.3 2777.03     270 2747.01   282.8  2746.2
     300 2749.06   334.4 2749.59   346.8 2746.87   364.2 2750.92   389.9 2745.65
   415.6 2745.04   430.4 2741.65   433.5 2741.25     445  2741.6   449.9 2742.33
   475.6 2765.76   492.7 2767.53   523.3 2775.78     538 2776.38   616.8 2800.37
   630.9 2802.28   645.1 2808.95   665.7 2814.38   673.4 2818.43   688.1 2819.98
#Mann= 4 ,-1,0
       0      .1       0   430.4    .045       0     445      .1       0
  606.89     .08       0
Bank Sta=430.4,445
XS Rating Curve= 0 ,0
Exp/Cntr(USF)=0,0
Exp/Cntr=0.3,0.1

Type RM Length L Ch R = 1 ,23256   ,221.2,218.3,213.3
XS GIS Cut Line= 4
2229531.37503605623314.8632876592229943.53686364623182.348738632
 2229974.0764393623160.9192329112230125.40624523623069.368060044
#Sta/Elev= 30
       0 2827.33    17.6 2820.63    55.5 2809.49    63.9 2805.89   110.1  2792.6
   122.7 2787.44   131.1 2782.19   143.7 2780.27   156.3 2773.65   173.1 2767.81
   256.3  2746.2   284.9 2742.61     295 2737.46   311.8 2737.02   316.7 2737.47
   324.4 2739.62   345.4 2740.44   374.8 2740.48     400 2737.81   408.4 2737.99
   429.4 2745.54   441.9 2751.32   467.9 2759.55   491.4  2764.2   505.4 2764.48
   547.5 2775.59   561.5 2775.89     613 2792.29   634.7 2803.42   647.1 2805.18
#Mann= 4 ,-1,0
       0      .1       0     295    .045       0   316.7      .1       0
  510.25     .08       0
#XS Ineff= 2 , 0
                          381.59         2754.76
Permanent Ineff=
       F       F
Bank Sta=295,316.7
XS Rating Curve= 0 ,0
Exp/Cntr=0.3,0.1

Type RM Length L Ch R = 1 ,23038   ,241.9,244.5,245.9
XS GIS Cut Line= 4
 2229653.5481474 623522.55523513 2229896.1773797 623433.40309861
2230019.18475794623336.3514056892230195.23201487623253.970317513
#Sta/Elev= 30
       0 2813.06    41.2 2799.66   109.3 2779.58   117.9 2775.92   126.4 2775.12
   134.9 2776.35   152.7 2769.86   171.4 2765.53   181.8 2764.18   207.3 2755.43
   224.3 2751.08   258.6 2743.28   272.9 2741.99   298.5 2735.78   315.6 2733.16
  331.12 2733.15   345.1 2735.45   369.7  2731.7   375.7 2732.81   395.4 2742.72
   425.1 2751.52   460.4 2757.81   472.5 2761.29   491.3 2760.99   502.5 2765.21
   535.2 2772.76   550.7 2779.32   557.6 2780.62   566.4 2784.79   609.5 2799.25
#Mann= 3 ,-1,0
       0      .1       0   315.6    .045       0  331.12      .1       0
Bank Sta=315.6,331.12
XS Rating Curve= 0 ,0
Exp/Cntr(USF)=0,0
Exp/Cntr=0.3,0.1

Type RM Length L Ch R = 1 ,22793   ,260.1,263.6,264.7
XS GIS Cut Line= 4
2229732.09389352623674.2082893622229969.02739009623638.142193238
2230200.16124536623544.6354707572230339.44380397623488.614211279
#Sta/Elev= 30
       0 2807.52    92.3 2779.47   101.2 2775.85   109.3 2770.64   125.5 2769.62
   137.6 2764.59   153.8 2759.98   218.6 2737.16     228 2735.68   247.4 2729.55
     252 2728.64   268.9 2728.92   312.1 2732.18   341.1 2731.54  349.482728.502
   362.6  2728.5   368.2 2731.06   372.5 2731.54   389.8 2730.35   411.3 2727.22
   445.9 2732.59   450.2 2735.35   480.4 2762.21   485.5 2765.28   501.9 2766.39
   510.6 2771.58     558 2784.46   583.9  2793.2   596.8 2796.06   639.1 2809.56
#Mann= 3 ,-1,0
       0      .1       0  349.48    .045       0   362.6      .1       0
#XS Ineff= 2 , 0
          291.12 2742.76
Permanent Ineff=
       F       F
Bank Sta=349.48,362.6
XS Rating Curve= 0 ,0
Exp/Cntr=0.3,0.1