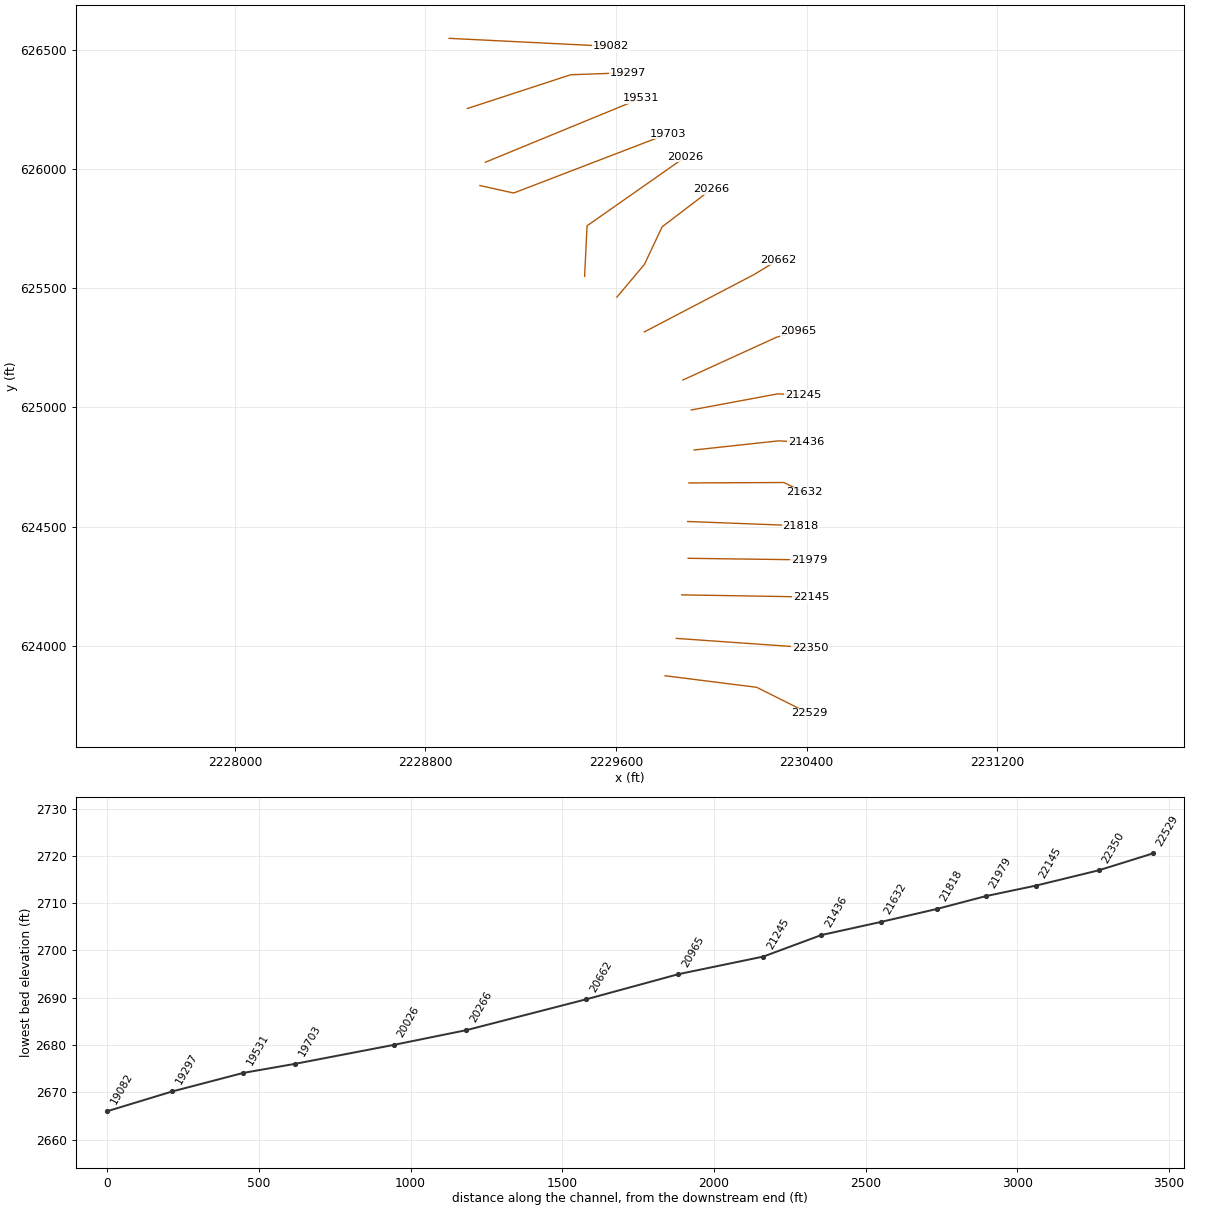
HEC-RAS study BIRCHFK.prj: BIRCHFK

--- BIRCHFK.g01 (geometry) --- (continued)

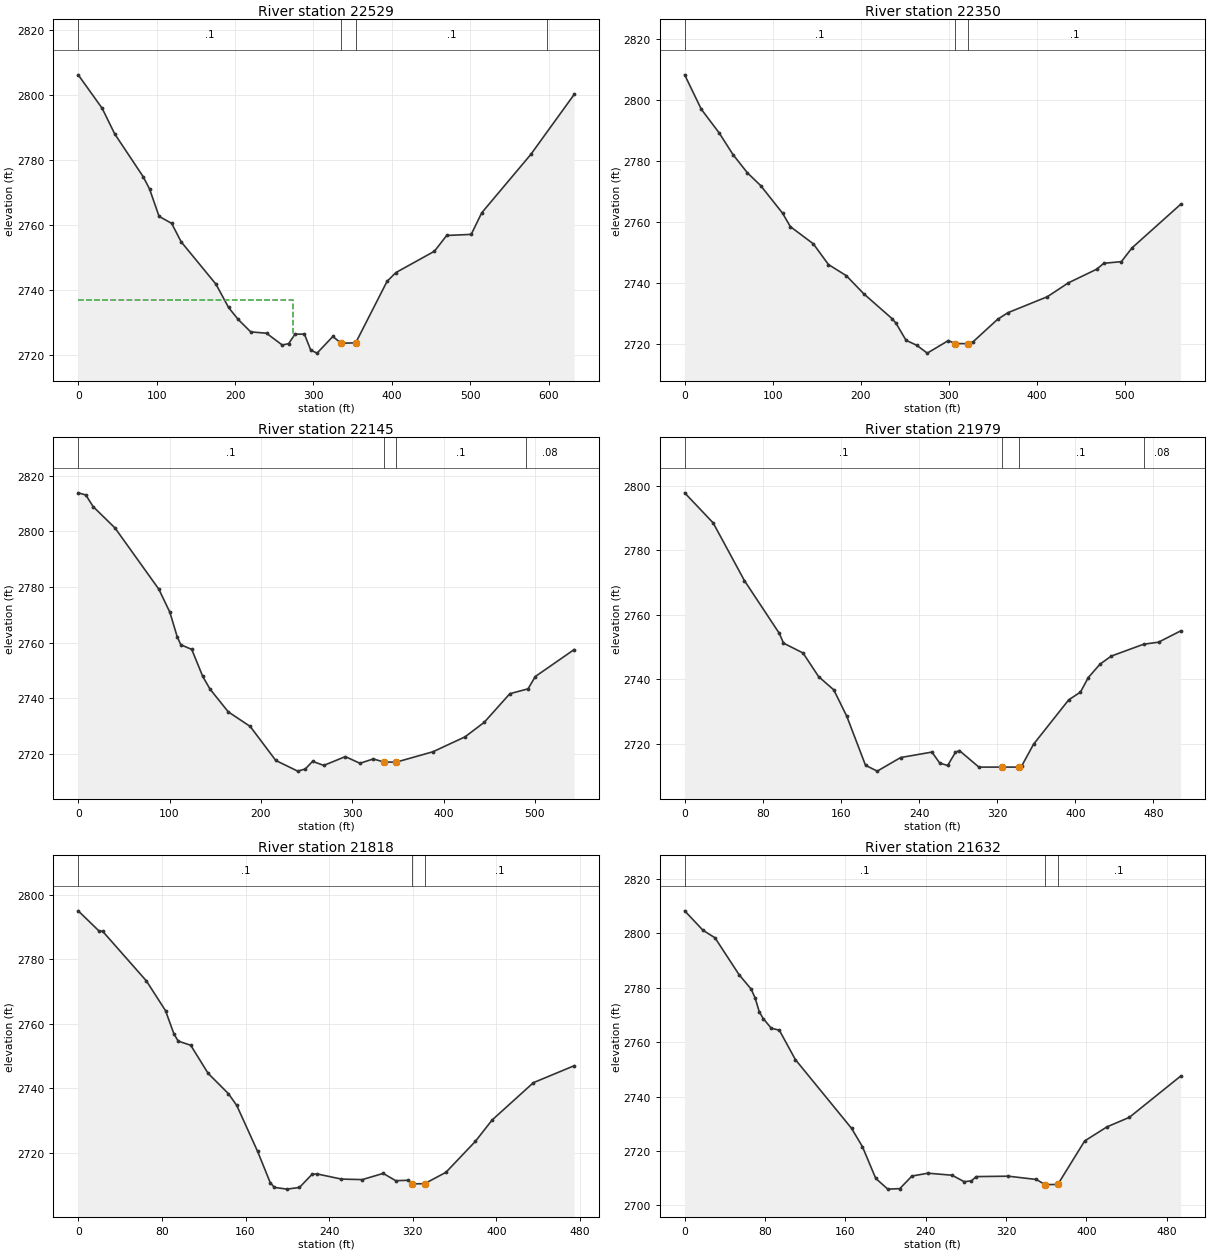
Type RM Length L Ch R = 1 ,22529   ,178.5,179.1,179.4
XS GIS Cut Line= 3
2229805.89673513623873.5212409242230190.71798264623824.995394464
2230409.64854574623715.530112914
#Sta/Elev= 30
       0 2806.09    30.5 2795.82    46.6 2787.91    82.9 2774.76      91 2770.99
   103.1 2762.59   119.2 2760.41   131.3 2754.75   175.7 2741.72   191.8 2734.55
   203.9 2730.92     220 2727.06   240.2 2726.64   260.3    2723   268.4 2723.44
   276.5 2726.33   288.5 2726.39   296.6 2721.44   304.7 2720.52   324.8 2725.64
   335.3 2723.58  353.912723.669     394 2742.61   405.3  2745.3   454.4 2751.85
     470  2756.7   501.3 2757.03   514.7 2763.66   577.3 2781.61   632.6 2800.05
#Mann= 4 ,-1,0
       0      .1       0   335.3    .045       0  353.91      .1       0
  597.87     .08       0
#XS Ineff= 2 , 0
          274.44 2736.72
Permanent Ineff=
       F       F
Bank Sta=335.3,353.91
XS Rating Curve= 0 ,0
Exp/Cntr(USF)=0,0
Exp/Cntr=0.3,0.1

Type RM Length L Ch R = 1 ,22350   ,206.4,205.9,206.8
XS GIS Cut Line= 2
2229853.29407353624030.3838608772230415.29108602623990.886078875
#Sta/Elev= 30
       0 2808.23    18.9 2796.93      39 2789.25      55 2782.03    71.3 2776.07
    86.3 2771.91   111.2 2762.85     120 2758.45   146.2 2752.78   163.3 2746.01
   183.7 2742.33   203.4 2736.42   235.5 2728.28   239.9 2726.83   251.5 2721.14
   263.5 2719.54   275.6 2716.94   299.6 2721.07   307.3 2720.06   322.3 2720.06
   327.7 2720.68   355.5 2728.04   367.2  2730.2   411.9 2735.43     436 2740.01
     468 2744.46   476.2 2746.41   496.1 2746.95   508.1 2751.44   563.4 2765.75
#Mann= 3 ,-1,0
       0      .1       0   307.3    .045       0   322.3      .1       0
Bank Sta=307.3,322.3
XS Rating Curve= 0 ,0
Exp/Cntr(USF)=0,0
Exp/Cntr=0.3,0.1

Type RM Length L Ch R = 1 ,22145   ,165.4,165.7,165.2
XS GIS Cut Line= 2
2229875.86423467624213.2021661472230418.67661019624204.174101689
#Sta/Elev= 30
       0  2813.9     8.3 2813.13    16.3 2808.96    40.3 2801.24    88.3 2779.19
   100.3 2770.94   108.3 2762.16   112.3 2759.22   124.3 2757.53   136.3 2747.83
   144.3 2743.24   164.3 2735.05   188.3  2729.8   216.3 2717.55   240.3 2713.72
   248.5 2714.48   256.6 2717.25   268.8 2715.77   292.4 2718.95   308.4 2716.54
     323 2718.11   334.8 2716.97   348.4 2716.98   388.4  2720.7   423.4 2726.05
   444.4 2731.27   472.5 2741.59   492.4 2743.34   500.4 2747.78   542.9 2757.48
#Mann= 4 ,-1,0
       0      .1       0   334.8    .045       0   348.4      .1       0
     490     .08       0
Bank Sta=334.8,348.4
XS Rating Curve= 0 ,0
Exp/Cntr(USF)=0,0
Exp/Cntr=0.3,0.1

Type RM Length L Ch R = 1 ,21979   ,160.2,160.3,159.9
XS GIS Cut Line= 2
2229902.94842805624366.6792619282230410.77705379624359.908213585
#Sta/Elev= 30
       0 2797.83    29.2 2788.49    61.2 2770.59      97 2754.19   101.2  2751.2
   121.2 2748.14   137.2  2740.8   152.7  2736.7     166 2728.52   185.2  2713.3
   197.2 2711.49   221.2 2715.71   253.2  2717.4   261.2 2713.99   269.3 2713.24
   277.3 2717.31   281.3 2717.88   301.3 2712.74   325.3 2712.74   342.2 2712.74
   345.3 2713.18   357.3 2719.84   393.3 2733.61   405.3    2736   413.3  2740.5
   425.4 2744.69   436.9 2747.18     470 2750.86   485.3  2751.5   507.9 2754.99
#Mann= 4 ,-1,0
       0      .1       0   325.3    .045       0   342.2      .1       0
     470     .08       0
Bank Sta=325.3,342.2
XS Rating Curve= 0 ,0
Exp/Cntr(USF)=0,0
Exp/Cntr=0.3,0.1

Type RM Length L Ch R = 1 ,21818   ,186.1,186.7,187
XS GIS Cut Line= 2
2229900.69141193624521.2848657672230374.66479596624503.228736851
#Sta/Elev= 30
       0 2794.97    19.5 2788.85    23.5 2788.59    65.2 2773.27    83.5 2764.06
    91.5 2756.89    95.6 2754.63   107.6 2753.34   124.2 2744.66   143.6 2738.37
   151.6 2734.72   171.6 2720.45   183.6 2710.84   187.6 2709.33   199.6 2708.79
   211.6 2709.31   223.6 2713.37   228.2 2713.51   251.7  2711.9   271.7 2711.74
   291.7 2713.66   303.7  2711.4   315.7 2711.53   319.7 2710.43   331.2 2710.46
   351.7    2714   379.8 2723.57   395.8 2730.18   435.3 2741.75   474.3    2747
#Mann= 3 ,-1,0
       0      .1       0   319.7    .045       0   331.2      .1       0
Bank Sta=319.7,331.2
XS Rating Curve= 0 ,0
Exp/Cntr(USF)=0,0
Exp/Cntr=0.3,0.1

Type RM Length L Ch R = 1 ,21632   ,193.4,195.4,194.4
XS GIS Cut Line= 3
2229905.96628155624683.1486293682230305.05724172624684.923395256
2230389.91312312624643.031726055
#Sta/Elev= 30
       0 2808.18    18.2 2801.05    30.2 2798.27    54.2 2784.71    66.2 2779.43
    70.2 2776.11    74.2 2771.18    78.2 2768.61    86.2 2765.08    94.2 2764.36
   110.2 2753.57   166.2 2728.29     177 2721.56   190.2 2709.95   202.2 2706.01
   214.2  2706.2   226.2 2710.81   242.2 2711.86   266.2 2711.11   278.2 2708.75
   285.5 2709.04   290.2 2710.61   322.2 2710.76   350.2 2709.55   358.6 2707.68
  371.412707.713   398.2  2723.7   420.4 2728.87   442.7 2732.37   493.7  2747.5
#Mann= 3 ,-1,0
       0      .1       0   358.6    .045       0  371.41      .1       0
Bank Sta=358.6,371.41
XS Rating Curve= 0 ,0
Exp/Cntr=0.3,0.1

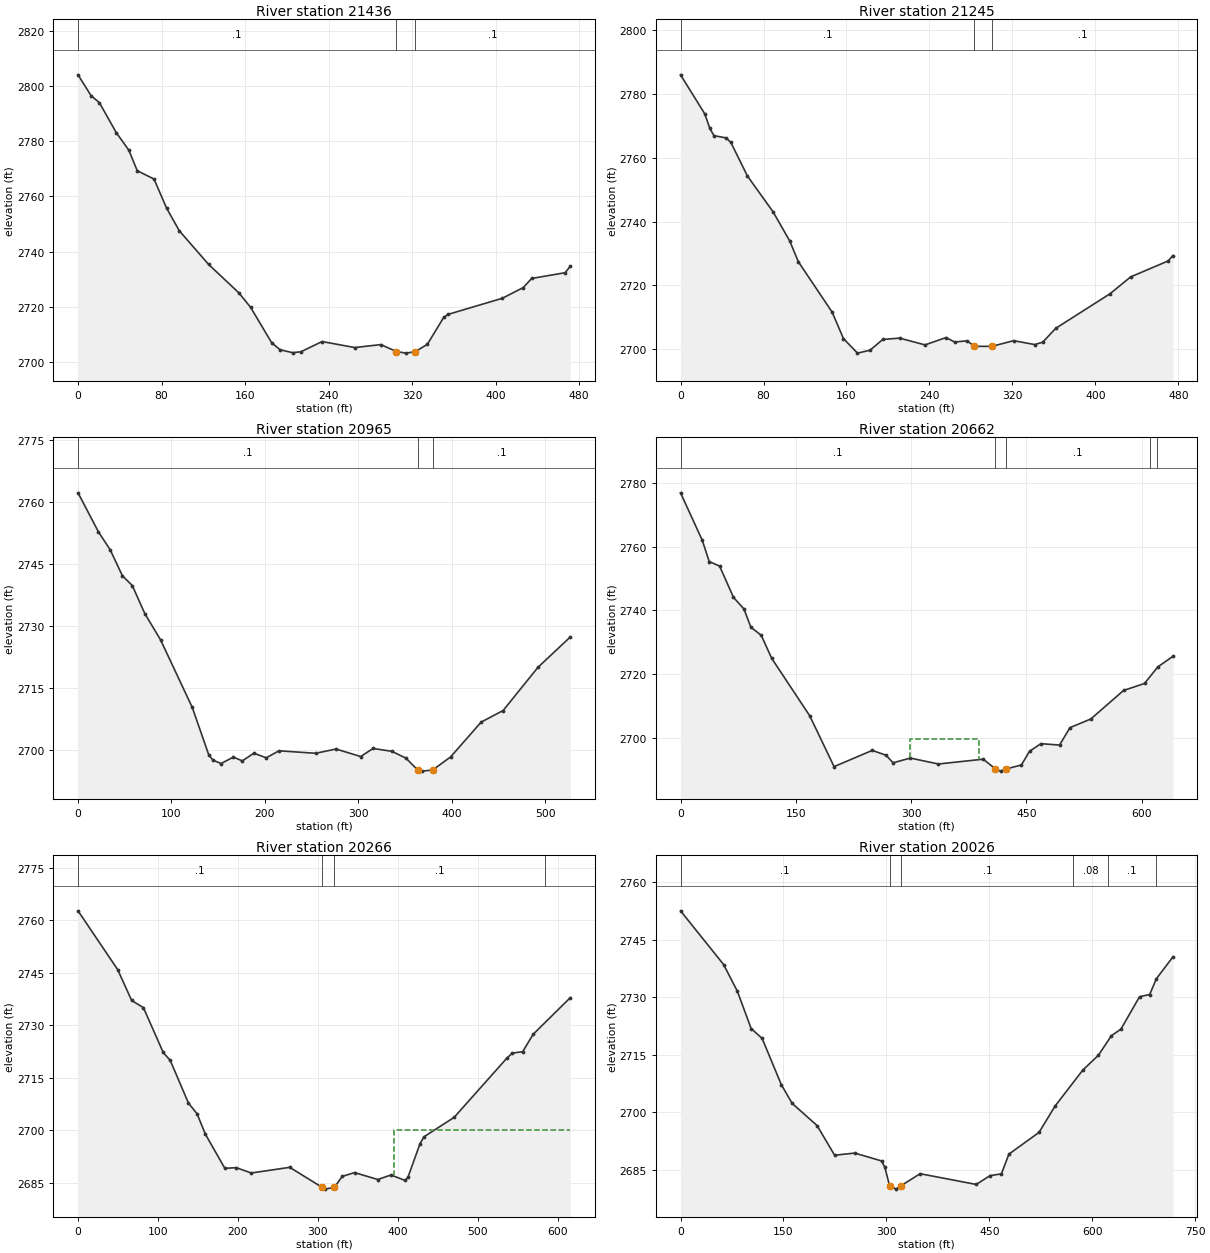
Type RM Length L Ch R = 1 ,21436   ,190.7,191.3,192.1
XS GIS Cut Line= 3
2229927.77560531624821.4680089862230282.12713527624859.837282932
2230397.23495711624854.194742645
#Sta/Elev= 30
       0 2803.98    12.5 2796.44    20.5 2793.88    36.6 2783.09    48.7 2776.69
    56.7 2769.28    72.8 2766.26    84.9 2755.69      97 2747.55   125.1 2735.36
   154.2 2725.03   165.4 2719.79   185.5 2707.03   193.5 2704.49   205.6 2703.41
   213.6 2703.75   233.8 2707.44   265.1 2705.27   290.1 2706.34     305 2703.83
   314.2 2703.25   323.2 2703.79   334.7 2706.45   350.4 2716.22   354.5 2717.27
   406.5  2723.1   426.6 2726.99   434.6 2730.28   466.6 2732.35   471.7 2734.71
#Mann= 3 ,-1,0
       0      .1       0     305    .045       0   323.2      .1       0
Bank Sta=305,323.2
XS Rating Curve= 0 ,0
Exp/Cntr(USF)=0,0
Exp/Cntr=0.3,0.1

Type RM Length L Ch R = 1 ,21245   ,278.7,280.3,282
XS GIS Cut Line= 3
2229916.49052473624989.6157095112230279.87011916625057.326192944
2230384.82136848625051.683652658
#Sta/Elev= 30
       0 2786.06    23.4  2773.8    28.2 2769.28    32.2 2766.97    43.9 2766.26
    48.5 2764.85    64.5 2754.29    89.2 2743.07   105.2 2733.96   113.6 2727.39
   146.2 2711.55   157.1 2703.26   170.6  2698.7   182.8 2699.62     195    2703
   211.3 2703.41   235.7 2701.28     256 2703.59   264.2 2702.19   276.4 2702.56
  283.292700.837   300.2 2700.82   321.1 2702.61   341.5 2701.39   349.2 2702.13
   361.8  2706.5     414 2717.31     434 2722.63   470.1 2727.63   474.7 2729.34
#Mann= 3 ,-1,0
       0      .1       0  283.29    .045       0   300.2      .1       0
Bank Sta=283.29,300.2
XS Rating Curve= 0 ,0
Exp/Cntr(USF)=0,0
Exp/Cntr=0.3,0.1

Type RM Length L Ch R = 1 ,20965   ,302.1,303,302.8
XS GIS Cut Line= 3
2229880.92285407625115.4750076052230273.54447583625294.765668296
2230365.59748615625320.192659787
#Sta/Elev= 30
       0 2762.33    21.9 2752.86    34.4 2748.56    47.5 2742.26    58.1 2739.89
    71.5  2733.1    88.3 2726.77   122.3 2710.39   139.9 2698.95   144.3 2697.65
   153.1 2696.81   166.3 2698.36   175.8 2697.45   188.3 2699.31   201.5 2698.19
   215.1 2699.89   254.5 2699.29   276.2 2700.32   302.6  2698.5   315.8 2700.45
   335.8 2699.78     351 2698.12  363.672695.246   368.6 2694.97   379.7 2695.25
   398.9 2698.41   431.6 2706.84   455.1 2709.64   492.4 2720.09   527.1 2727.46
#Mann= 3 ,-1,0
       0      .1       0  363.67    .045       0   379.7      .1       0
Bank Sta=363.67,379.7
XS Rating Curve= 0 ,0
Exp/Cntr=0.3,0.1

Type RM Length L Ch R = 1 ,20662   ,389.8,395.3,399.2
XS GIS Cut Line= 3
2229719.10694315 625317.325435092230180.23182184625558.503064458
2230282.97818894625621.156989731
#Sta/Elev= 30
       0 2776.83    28.3 2761.95    37.3 2755.32    50.9 2753.86    68.9 2744.08
    82.5 2740.47    91.5 2734.77     105 2732.21   118.6 2725.01   168.2 2706.97
   199.8 2691.08   249.5 2696.16   267.5 2694.64   276.6 2692.28   299.1 2693.76
   335.6  2691.9   393.9 2693.41   409.7 2690.39   416.5 2689.67  423.832690.357
   443.6  2691.6   454.2 2695.89     469 2698.27   493.2 2697.83   506.8 2703.29
   533.9    2706   576.5 2714.93   603.8 2717.13   621.2 2722.33   640.7 2725.61
#Mann= 5 ,-1,0
       0      .1       0   409.7    .045       0  423.83      .1       0
  610.39     .08       0  620.39      .1       0
#XS Ineff= 1 ,-1
  299.16  388.26 2699.61
Permanent Ineff=
       F
Bank Sta=409.7,423.83
XS Rating Curve= 0 ,0
Exp/Cntr=0.3,0.1

Type RM Length L Ch R = 1 ,20266   ,243.4,240.1,234.4
XS GIS Cut Line= 4
2229603.51629745625463.2560982952229719.28799651 625600.78173902
2229793.49465206625758.3167318422230001.74877076625917.436489023
#Sta/Elev= 30
       0 2762.69    49.6 2745.89    67.1 2737.06    81.8 2735.02   106.6  2722.2
   115.4 2719.92   138.1 2707.76   148.9 2704.69   159.4 2698.82   183.7 2689.08
   197.9 2689.28   216.8 2687.75   264.9 2689.37  305.27 2683.67   308.4 2683.14
   320.8 2683.64   330.5 2686.77     346 2687.87     375 2685.89   391.6 2687.18
   409.2 2685.62   412.7 2686.48   427.8 2696.09   432.8 2698.09   470.6 2703.66
   536.5 2720.57   543.5 2722.03   556.3 2722.42   569.4 2727.39     616 2737.89
#Mann= 4 ,-1,0
       0      .1       0  305.27    .045       0   320.8      .1       0
  583.91     .08       0
#XS Ineff= 2 , 0
                          394.73            2700
Permanent Ineff=
       F       F
Bank Sta=305.27,320.8
XS Rating Curve= 0 ,0
Exp/Cntr=0.3,0.1

Type RM Length L Ch R = 1 ,20026   ,323.8,323.8,319.4
XS GIS Cut Line= 3
2229468.08650778625550.4176634072229478.43248343625762.851765566
2229891.90149925626052.564684994
#Sta/Elev= 30
       0 2752.58    62.8 2738.57    82.8 2731.62   102.9 2721.89   118.9 2719.32
   146.9 2707.25   162.8 2702.35     199 2696.59   224.6 2688.85   253.9 2689.41
     293 2687.36   297.8 2685.69   304.6 2680.95   314.3 2680.01   321.9 2680.95
   349.2 2684.03     431 2681.23   451.1 2683.53   467.7 2683.99   478.6 2689.14
   522.5  2694.8   545.9 2701.67   586.2 2711.03   609.1 2714.93     628 2720.02
   641.9 2721.73     669 2730.18   683.8 2730.76   693.5 2734.86   717.6 2740.56
#Mann= 6 ,-1,0
       0      .1       0   304.6    .045       0   321.9      .1       0
  572.69     .08       0  622.69      .1       0  692.69     .08       0
Bank Sta=304.6,321.9
XS Rating Curve= 0 ,0
Exp/Cntr=0.3,0.1

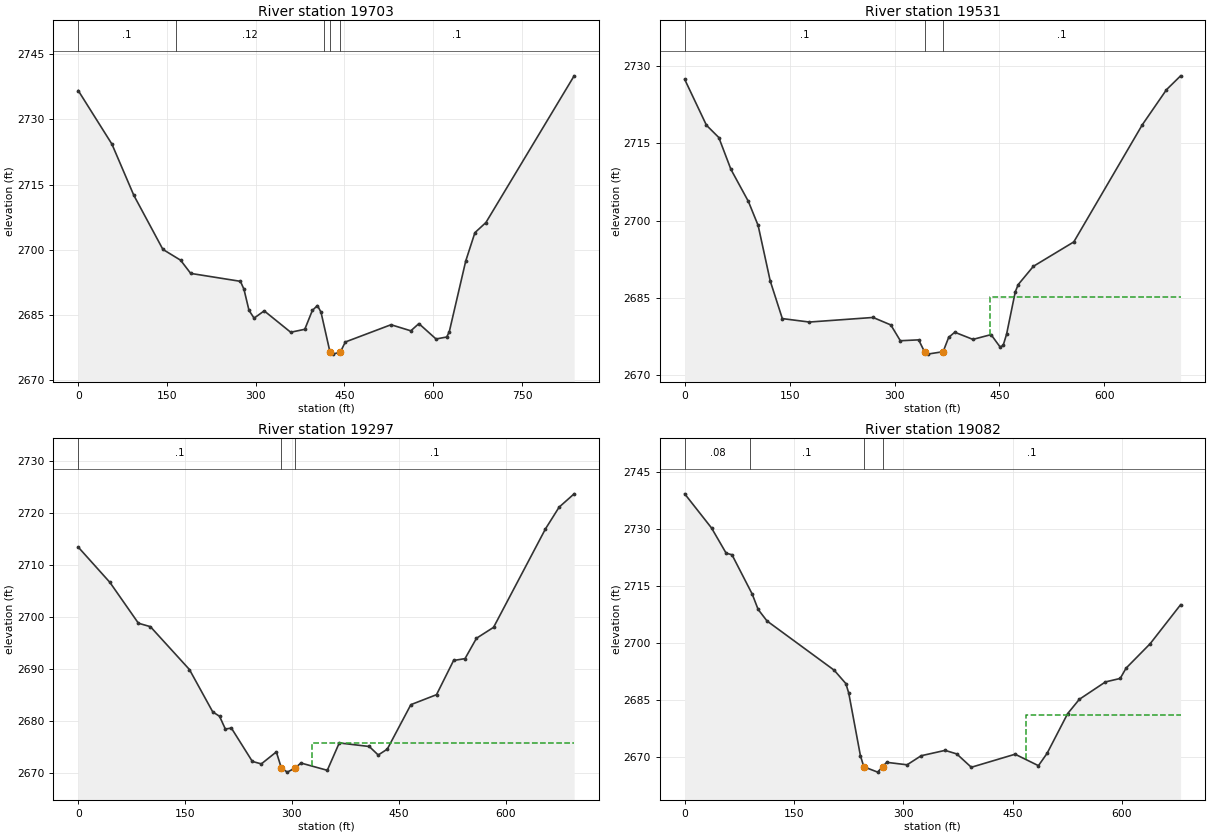
Type RM Length L Ch R = 1 ,19703   ,171.4,171.7,172.1
XS GIS Cut Line= 3
2229028.49847775625931.8659285192229170.18893382625900.518482485
2229817.20021996626148.790255073
#Sta/Elev= 30
       0 2736.63      57  2724.3    93.9 2712.56   143.1  2700.1     173 2697.62
   190.1 2694.58   274.1 2692.76   280.1 2690.94   288.6 2686.09   297.2 2684.29
   314.3 2685.97   359.1 2681.05   382.9 2681.73   395.7 2686.07   404.3  2687.2
   410.3 2685.66   425.5  2676.5     430 2676.02   442.9 2676.47   451.4 2678.81
   528.6 2682.78   562.1 2681.38   575.7 2683.04   604.7  2679.5   622.8 2679.96
   627.1 2681.18   654.9 2697.44   670.4 2703.95     689 2706.28   838.1 2740.01
#Mann= 5 ,-1,0
       0      .1       0  165.12     .12       0  415.12      .1       0
   425.5    .045       0   442.9      .1       0
Bank Sta=425.5,442.9
XS Rating Curve= 0 ,0
Exp/Cntr(USF)=0,0
Exp/Cntr=0.3,0.1

Type RM Length L Ch R = 1 ,19531   ,232.9,234,233.5
XS GIS Cut Line= 2
2229051.06863889626029.6699601442229706.85720992626299.257996035
#Sta/Elev= 30
       0 2727.45    31.1 2718.54    48.8 2716.15    66.1 2709.97    91.1 2703.73
     105 2699.08   122.3  2688.3   139.6 2680.99   178.2 2680.32   269.3 2681.21
   294.7 2679.76   308.3 2676.69   334.5 2676.86   342.9 2674.54   347.2 2674.09
  369.462674.563   377.4 2677.34   386.1 2678.34   412.1 2676.95     438 2677.88
   450.9 2675.48   455.3 2675.78   460.2 2677.96   472.6 2686.18   476.9 2687.61
   498.5 2691.14   556.3 2695.88   654.2 2718.62   688.8 2725.44     709 2728.13
#Mann= 3 ,-1,0
       0      .1       0   342.9    .045       0  369.46      .1       0
#XS Ineff= 2 , 0
                          436.68         2685.21
Permanent Ineff=
       F       F
Bank Sta=342.9,369.46
XS Rating Curve= 0 ,0
Exp/Cntr(USF)=0,0
Exp/Cntr=0.3,0.1

Type RM Length L Ch R = 1 ,19297   ,220.7,214.9,210.1
XS GIS Cut Line= 3
2228975.83476841626255.3715715882229409.68342152 626397.06202766
2229649.17790922 626405.83931255
#Sta/Elev= 30
       0 2713.44    44.5 2706.65    84.5  2698.8   101.3 2698.14   156.1  2689.9
   188.8 2681.76   198.4  2680.9   206.5 2678.46     215 2678.64   244.4 2672.23
     257 2671.75   278.1 2674.06   285.1 2670.97   293.5 2670.17  304.37 2670.96
   312.6 2671.92   349.6 2670.52   366.4 2675.78   408.5  2675.1   421.1 2673.46
   433.8 2674.59   466.9 2683.14   502.9 2685.06   526.9 2691.64   542.9 2691.99
     559 2695.91     583 2698.01   655.8 2716.93     675 2721.12   696.1 2723.68
#Mann= 3 ,0,0
       0      .1       0   285.1    .045       0  304.37      .1       0
#XS Ineff= 2 , 0
                          328.49         2675.84
Permanent Ineff=
       F       F
Bank Sta=285.1,304.37
XS Rating Curve= 0 ,0
Exp/Cntr(USF)=0,0
Exp/Cntr=0.3,0.1

Type RM Length L Ch R = 1 ,19082   ,247.4,247.6,246.9
XS GIS Cut Line= 2
2228899.34700009626550.037564305 2229578.9596301626516.182322589
#Sta/Elev= 30
       0  2739.3    36.9 2730.29    56.9 2723.66    64.9 2723.25    92.7 2712.87
   100.8 2708.84     113  2705.8   205.1 2692.84   221.1 2689.32   225.1 2686.83
   241.1 2670.35   245.8 2667.39   264.8 2665.98  271.482667.419   277.2 2668.56
   305.2 2667.91   324.5  2670.3   357.3 2671.71   373.3 2670.78   393.3 2667.26
   453.4  2670.7   485.4 2667.68   497.3 2670.94   525.5  2681.4   541.5 2685.16
   577.4 2689.75   597.6 2690.66   605.6 2693.36   638.7 2699.81   680.5 2710.09
#Mann= 4 ,-1,0
       0     .08       0      90      .1       0   245.8    .045       0
  271.48      .1       0
#XS Ineff= 2 , 0
                          468.01         2680.97
Permanent Ineff=
       F       F
Bank Sta=245.8,271.48
XS Rating Curve= 0 ,0
Exp/Cntr(USF)=0,0
Exp/Cntr=0.3,0.1