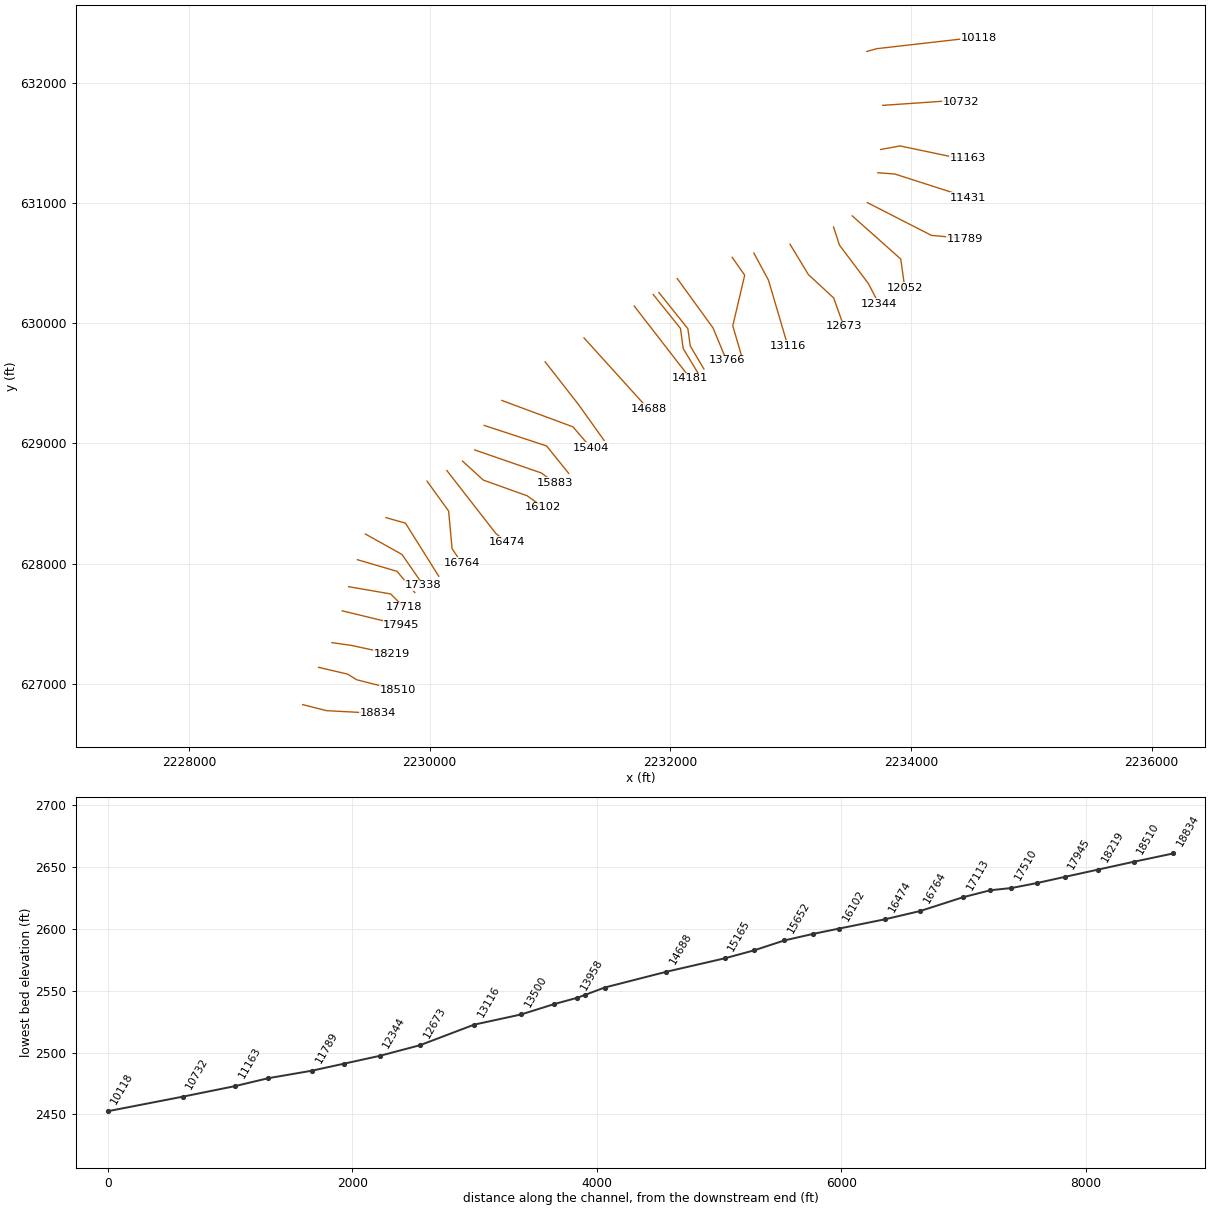
HEC-RAS study BIRCHFK.prj: BIRCHFK

--- BIRCHFK.g01 (geometry) --- (continued)

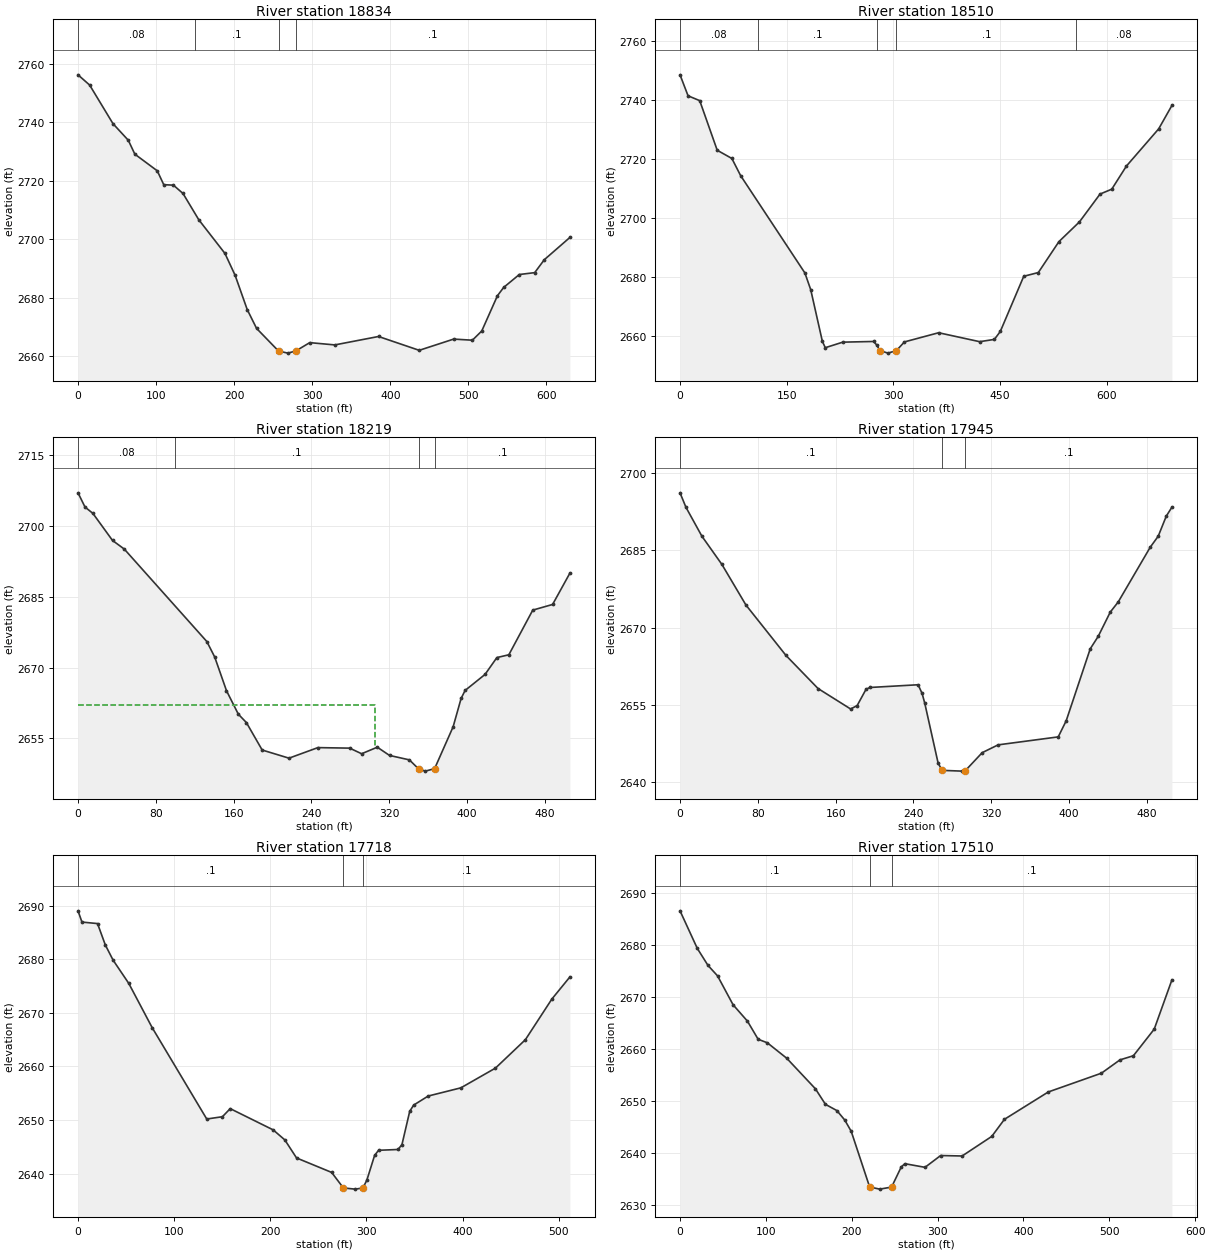
Type RM Length L Ch R = 1 ,18834   ,330.3,324.8,319.1
XS GIS Cut Line= 3
2228945.74122022626827.1489872442229143.85707915 626776.99307359
2229568.92844737626754.422912446
#Sta/Elev= 30
       0 2756.27    14.9 2752.77    44.8 2739.56    64.4 2733.89    72.8 2729.13
   101.5 2723.44   109.8  2718.7   122.2 2718.53   134.5 2715.68   154.7 2706.69
   188.2 2695.18   201.2 2687.71   216.7 2675.99   228.7 2669.54   256.8  2661.8
   268.8 2661.08  278.972661.825   296.8 2664.67   328.9 2663.89   384.9 2666.77
     437 2662.04   481.1 2665.88   505.1  2665.5   517.1 2668.65   537.2 2680.72
   545.2 2683.56   565.2 2687.97   584.9 2688.61   597.2 2693.03     630 2700.65
#Mann= 4 ,-1,0
       0     .08       0     150      .1       0   256.8    .045       0
  278.97      .1       0
Bank Sta=256.8,278.97
XS Rating Curve= 0 ,0
Exp/Cntr(USF)=0,0
Exp/Cntr=0.3,0.1

Type RM Length L Ch R = 1 ,18510   ,287.7,290.8,292.1
XS GIS Cut Line= 4
2229077.21393126627137.4088612032229318.39995898627081.136003291
2229394.38815396627033.875052756 2229738.2753461 626947.04370243
#Sta/Elev= 30
       0 2748.62    11.3 2741.51    27.7 2739.87    52.3 2723.06    72.9 2720.28
    85.2 2714.47   175.6 2681.48   183.8 2675.82   200.2 2658.28   204.3 2656.15
   228.9 2658.03   272.2 2658.26   277.12656.941   280.9 2655.19   292.5 2654.31
  304.39 2655.19   315.6 2658.11   363.7 2661.22   421.4 2658.19   442.1 2658.96
   450.4 2661.64   483.4 2680.35   503.9 2681.62   532.9  2692.1   561.8  2698.8
   590.7 2708.21   607.2 2709.87   627.8  2717.7   673.2 2730.32   691.8 2738.25
#Mann= 5 ,-1,0
       0     .08       0     110      .1       0   277.1    .045       0
  304.39      .1       0  557.15     .08       0
Bank Sta=280.9,304.39
XS Rating Curve= 0 ,0
Exp/Cntr(USF)=0,0
Exp/Cntr=0.3,0.1

Type RM Length L Ch R = 1 ,18219   ,273.6,273.6,271.1
XS GIS Cut Line= 3
2229188.99740144627342.501000039 2229348.2424273627319.930838895
2229685.54094662627247.204764097
#Sta/Elev= 30
       0 2707.07     7.2 2704.05    15.3 2702.71    35.5 2696.96    47.6 2695.13
   132.5 2675.51   140.6 2672.22   152.7 2665.08   164.9 2660.09   173.2 2658.31
   189.4 2652.49     217 2650.76   246.7    2653   279.4 2652.89   291.7  2651.7
   307.8 2653.09   320.4 2651.34   340.8  2650.4   350.2  2648.5   357.2 2648.01
  366.752648.537   385.8 2657.42     394 2663.43   398.1 2665.13   418.6 2668.53
   430.8 2672.11   443.1  2672.7   467.7 2682.18   488.1 2683.38   505.9 2690.03
#Mann= 4 ,-1,0
       0     .08       0     100      .1       0   350.2    .045       0
  366.75      .1       0
#XS Ineff= 2 , 0
          305.85 2662.09
Permanent Ineff=
       F       F
Bank Sta=350.2,366.75
XS Rating Curve= 0 ,0
Exp/Cntr(USF)=0,0
Exp/Cntr=0.3,0.1

Type RM Length L Ch R = 1 ,17945   ,226.6,227.2,227.8
XS GIS Cut Line= 2
2229274.26245466627607.0734445652229765.79040847627487.953149636
#Sta/Elev= 30
       0 2696.21     6.1 2693.39    22.5 2687.77    43.1 2682.27    67.8 2674.38
     109 2664.57   141.9 2658.15   175.4 2654.17   182.1 2654.82   191.3 2658.01
   195.3 2658.35   244.8 2658.88   248.9  2657.2   251.6 2655.33   265.4 2643.63
   269.5 2642.23   290.1 2642.08   293.4 2642.18   310.7 2645.67   327.1 2647.19
   388.9 2648.74   397.1 2651.88   421.8 2665.87     430 2668.29   442.4 2673.01
   450.6 2674.99   483.5 2685.63   491.7 2687.77     500 2691.68   505.8 2693.42
#Mann= 3 ,-1,0
       0      .1       0   269.5    .045       0   293.4      .1       0
Bank Sta=269.5,293.4
XS Rating Curve= 0 ,0
Exp/Cntr(USF)=0,0
Exp/Cntr=0.3,0.1

Type RM Length L Ch R = 1 ,17718   ,209.7,208,206.3
XS GIS Cut Line= 3
2229328.18006183627807.6970991812229676.76366173627747.510002796
2229788.36056961627635.913094916
#Sta/Elev= 30
       0 2689.06     4.1 2686.96    20.3 2686.68    28.4 2682.69    36.5 2679.85
    52.8 2675.51    77.1 2667.26   133.9 2650.19   150.2 2650.62   158.3 2652.13
     203 2648.16   215.1 2646.29   227.3 2642.92   263.8 2640.22     276 2637.32
   288.2  2637.1   296.3 2637.31   300.4 2638.77   308.5 2643.41   312.6 2644.35
   332.8  2644.5   336.9  2645.4     345 2651.63   349.1 2652.79   364.2 2654.48
   398.2 2656.01   434.2  2659.7   465.3    2665   492.8 2672.58   511.6 2676.72
#Mann= 3 ,-1,0
       0      .1       0     276    .045       0   296.3      .1       0
Bank Sta=276,296.3
XS Rating Curve= 0 ,0
Exp/Cntr(USF)=0,0
Exp/Cntr=0.3,0.1

Type RM Length L Ch R = 1 ,17510   ,174.3,171.8,168.8
XS GIS Cut Line= 3
2229400.90613663628032.1448127832229729.42737107627935.594678999
2229877.38731635627758.795083368
#Sta/Elev= 30
       0 2686.59    20.1 2679.37    32.6 2676.09    43.7 2674.09    61.8 2668.53
    78.5 2665.39      91  2661.9   101.7 2661.22   124.3 2658.25   157.7 2652.38
   169.4 2649.39   182.7 2648.19   191.9 2646.37   199.4 2644.21   220.9 2633.49
   232.7 2633.09   246.4 2633.48   257.7 2637.35   261.9 2637.98   285.4 2637.28
   303.6 2639.55   328.6 2639.46   363.1 2643.22   377.9 2646.51     429 2651.77
   490.9 2655.38   512.5 2657.94   528.1 2658.73   552.4 2663.85     573 2673.32
#Mann= 3 ,-1,0
       0      .1       0   220.9    .045       0   246.4      .1       0
Bank Sta=220.9,246.4
XS Rating Curve= 0 ,0
Exp/Cntr(USF)=0,0
Exp/Cntr=0.3,0.1

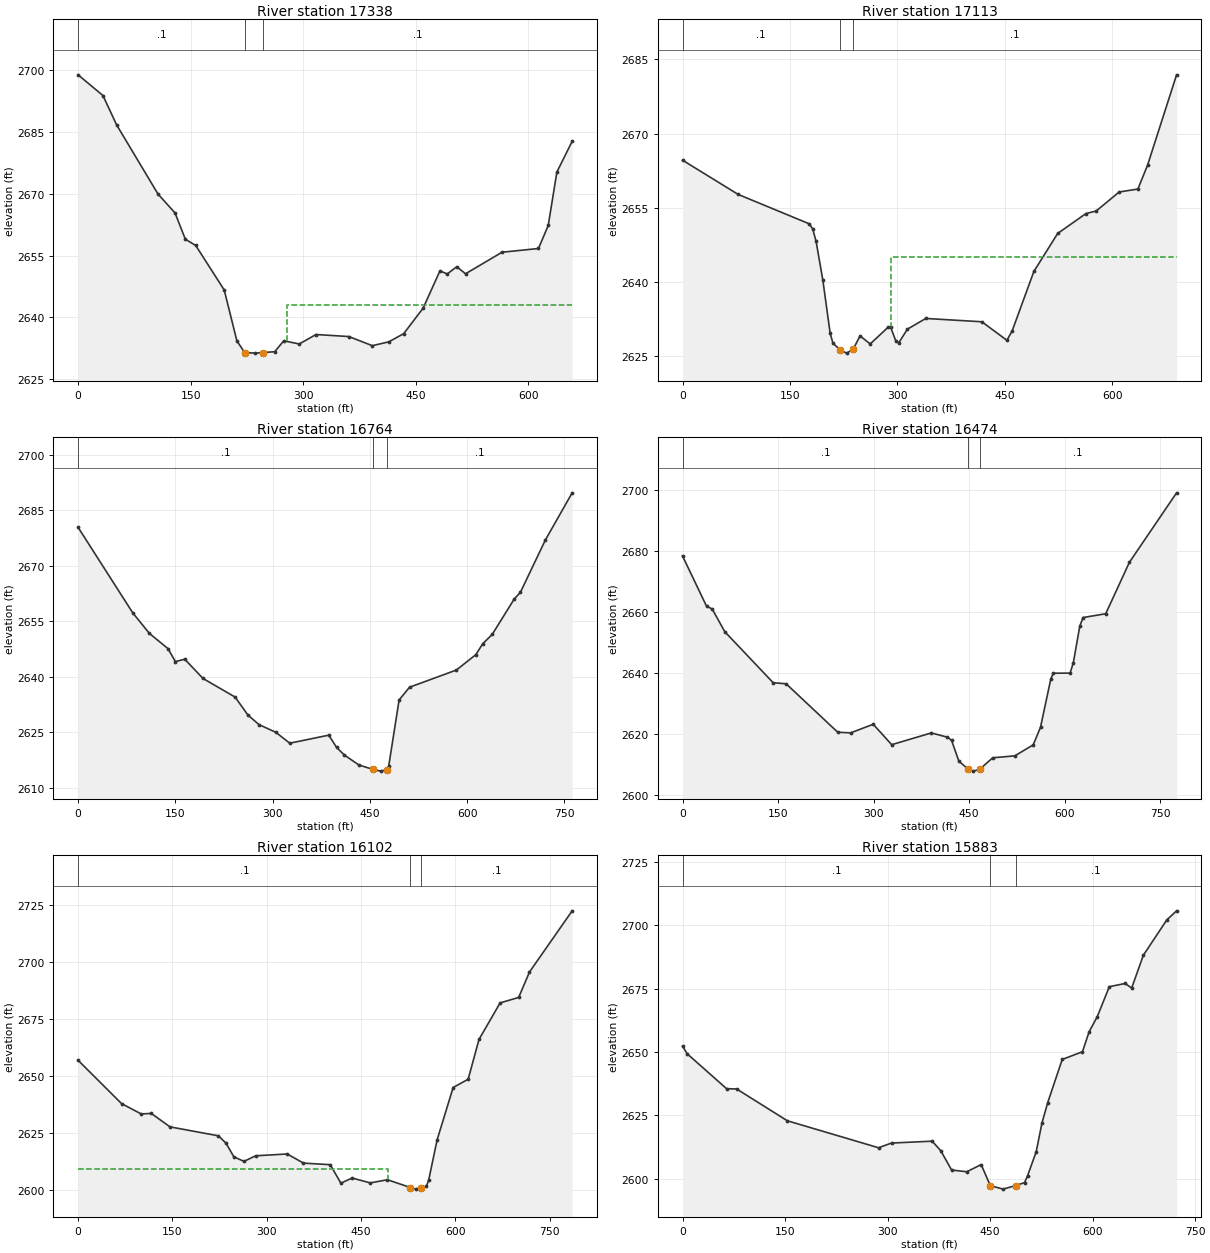
Type RM Length L Ch R = 1 ,17338   ,230.6,225.5,219.6
XS GIS Cut Line= 3
2229467.36272222628245.3074458132229770.80599983 628076.03123723
2229947.60559546627820.236077594
#Sta/Elev= 30
       0 2698.92    33.1 2693.88    51.3 2686.76   106.5 2669.95   129.2 2665.35
   142.9 2658.98   156.7 2657.47   194.7 2646.65   211.6 2634.28     222 2631.44
   235.9 2631.31   246.6 2631.44     262 2631.66   274.1 2634.31   294.7 2633.53
     317 2635.83   360.7 2635.34   392.1 2633.12   414.1 2634.06   433.9 2636.04
   459.8 2642.25   482.2  2651.3   491.9 2650.54   504.6  2652.3   516.3 2650.59
   564.9 2655.82   613.5 2656.73   626.5 2662.32     638 2675.29   658.4 2682.78
#Mann= 3 ,-1,0
       0      .1       0     222    .045       0   246.6      .1       0
#XS Ineff= 2 , 0
                          277.98         2642.91
Permanent Ineff=
       F       F
Bank Sta=222,246.6
XS Rating Curve= 0 ,0
Exp/Cntr(USF)=0,0
Exp/Cntr=0.3,0.1

Type RM Length L Ch R = 1 ,17113   ,352.5,348.7,344.4
XS GIS Cut Line= 3
2229637.32420432628382.1648029652229799.63677987628336.200117971
2230076.33439282627894.807359688
#Sta/Elev= 30
       0 2664.63    77.8  2657.7     177 2651.76   181.7 2650.72   186.4 2648.25
   195.9 2640.35   206.1 2629.61     210 2627.63   219.5 2626.33   228.9 2625.62
     238 2626.36   247.8  2629.1     262 2627.48   287.4 2630.91   290.3 2630.94
   297.7 2628.09   301.9 2627.71   313.9 2630.47   339.6 2632.63   417.8 2631.96
   452.8 2628.21   460.2 2630.15   490.5 2642.16   523.7 2649.82     563 2653.83
   577.5 2654.37   609.5  2658.2   635.6  2658.8   649.1 2663.62   689.6 2681.89
#Mann= 3 ,-1,0
       0      .1       0   219.5    .045       0     238      .1       0
#XS Ineff= 2 , 0
                          291.12          2645.1
Permanent Ineff=
       F       F
Bank Sta=219.5,238
XS Rating Curve= 0 ,0
Exp/Cntr=0.3,0.1

Type RM Length L Ch R = 1 ,16764   ,283.1,289.8,294.8
XS GIS Cut Line= 4
2229978.95304149628685.4255881272230158.26043281628437.153815539
2230187.10008316628123.6793552012230266.09564716628007.066855956
#Sta/Elev= 30
       0 2680.37    84.1 2657.32   109.9 2651.72   138.5 2647.63     150 2644.11
   164.4 2644.75   192.7 2639.54   242.1 2634.52   261.7  2629.7     279 2627.07
   304.7 2625.02   326.4 2622.06   386.6 2624.23   398.6 2620.91   410.7 2618.84
   433.1 2616.16   455.1 2614.96   466.9 2614.51  476.042614.947     479 2615.89
     495 2633.74   511.1 2637.18   583.4 2641.83   613.3 2645.98   624.1 2648.96
   638.6 2651.45   672.4 2660.98     682 2662.81   720.7 2677.01   761.9 2689.71
#Mann= 3 ,-1,0
       0      .1       0   455.1    .045       0  476.04      .1       0
Bank Sta=455.1,476.04
XS Rating Curve= 0 ,0
Exp/Cntr(USF)=0,0
Exp/Cntr=0.3,0.1

Type RM Length L Ch R = 1 ,16474   ,365.6,372.3,374.6
XS GIS Cut Line= 3
     2230143.616       628773.572230551.43530497628249.540764057
2230638.87999423628179.721939506
#Sta/Elev= 30
       0  2678.4    37.7 2661.92    46.5 2661.02    66.4 2653.54   142.4 2636.79
   162.7 2636.45   243.8 2620.54   264.1 2620.34   299.5 2623.16   328.5 2616.46
   390.8 2620.32   416.1 2618.91   422.5 2617.91   433.9 2611.09  448.742608.374
   456.7 2607.78   466.8 2608.39   487.1 2612.16   521.9 2612.79   550.8 2616.41
   562.2 2622.18   578.3 2637.93   582.1 2639.92   608.7 2639.95   613.8  2643.4
   623.9 2655.37     629 2658.19   664.6 2659.43   701.8 2676.31   775.9 2699.12
#Mann= 3 ,-1,0
       0      .1       0  448.74    .045       0   466.8      .1       0
Bank Sta=448.74,466.8
XS Rating Curve= 0 ,0
Exp/Cntr=0.3,0.1

Type RM Length L Ch R = 1 ,16102   ,217.7,218.2,219.9
XS GIS Cut Line= 4
2230274.23237701628851.7229252022230446.65693632628694.202873016
 2230811.2060748628563.4963496492230945.48006049628467.868526606
#Sta/Elev= 30
       0 2656.89      69 2637.91   100.2 2633.36   116.4 2633.56   146.1 2627.68
   223.2 2623.74   235.2 2620.52   247.6 2614.54   263.7 2612.52   282.4 2614.98
   332.5 2615.77   358.4 2611.76   400.9 2611.07   417.9 2602.96   435.7 2605.22
   464.6 2603.07     492 2604.46   528.4 2601.05   536.9 2600.34   544.7 2601.05
   553.9 2601.54   557.7 2604.54   570.9 2621.96   596.4 2644.94   620.3 2648.59
   637.5 2666.05   671.1  2682.1   700.6 2684.49   717.8 2695.66   785.7 2722.52
#Mann= 3 ,-1,0
       0      .1       0   528.4    .045       0   544.7      .1       0
#XS Ineff= 2 , 0
          492.51 2609.36
Permanent Ineff=
       F       F
Bank Sta=528.4,544.7
XS Rating Curve= 0 ,0
Exp/Cntr=0.3,0.1

Type RM Length L Ch R = 1 ,15883   ,230.8,231.6,230
XS GIS Cut Line= 3
2230375.18475936628944.9824412872230929.40760524 628753.13607156
2231039.75061528628672.886609713
#Sta/Elev= 30
       0  2652.3     6.9  2649.3    64.5 2635.54    79.2 2635.43   153.4 2622.88
   286.8 2612.24   305.8 2614.09   365.4 2614.83     378 2611.02   393.7 2603.44
   415.9 2602.77     437 2605.59   450.3  2597.3   469.1 2595.91   487.5 2597.32
   500.5 2598.49   504.8 2601.16   517.5 2610.63   525.9 2621.96   534.4 2630.08
   555.6 2647.08   585.2 2650.12   594.9 2657.96   606.8 2663.92   624.5 2675.79
   647.6 2677.05   657.2 2675.27   674.3 2688.19   708.6 2702.14   722.9 2705.72
#Mann= 3 ,-1,0
       0      .1       0   450.3    .045       0   487.5      .1       0
Bank Sta=450.3,487.5
XS Rating Curve= 0 ,0
Exp/Cntr(USF)=0,0
Exp/Cntr=0.3,0.1

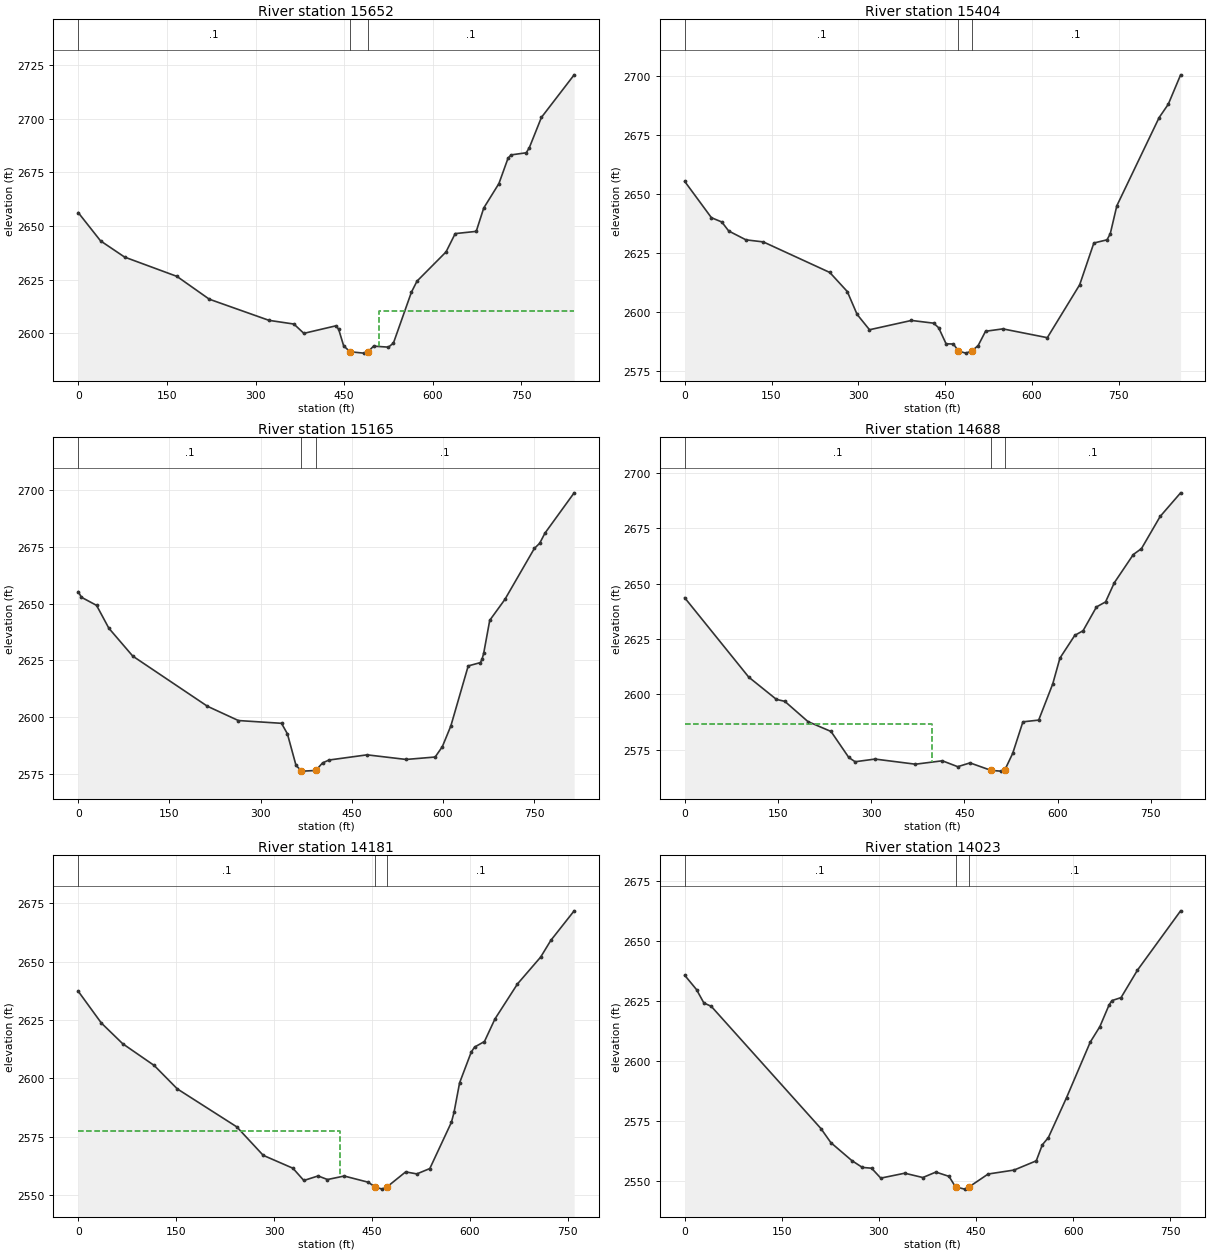
Type RM Length L Ch R = 1 ,15652   ,248.6,247.8,244.3
XS GIS Cut Line= 3
2230453.50815111629148.9878504032230972.47711797628978.192333836
2231156.03525904628750.005145332
#Sta/Elev= 30
       0 2656.29    37.8 2643.08    78.6  2635.5     167 2626.51   221.8 2615.86
   322.8 2605.99     365 2604.26   381.8 2599.92   436.5 2603.46   440.8 2601.73
   449.2 2594.08     460 2591.33   482.9 2590.69  490.292591.269   499.7 2593.95
     525 2593.48   533.4 2595.39   563.9 2619.18   573.3 2624.29   622.4 2637.92
   637.9 2646.47   673.5 2647.51   686.2 2658.41   711.9 2669.83   727.3 2681.65
   732.5  2683.2   758.1 2684.19   763.3 2686.53   783.8 2700.69   839.2 2720.57
#Mann= 3 ,-1,0
       0      .1       0     460    .045       0  490.29      .1       0
#XS Ineff= 2 , 0
                          509.03         2610.34
Permanent Ineff=
       F       F
Bank Sta=460,490.29
XS Rating Curve= 0 ,0
Exp/Cntr=0.3,0.1

Type RM Length L Ch R = 1 ,15404   ,244.8,239.1,231.8
XS GIS Cut Line= 3
2230600.88637081 629356.260933252231191.47225408629136.828811013
2231339.43219936628965.044806748
#Sta/Elev= 30
       0 2655.35    46.2 2639.97    64.1 2638.16    76.1 2634.34   105.9  2630.6
   135.8 2629.73   250.7  2616.8   280.9 2608.74   297.9 2599.05   319.3 2592.56
   391.8  2596.5   430.2 2595.34   438.8  2593.4   451.6 2586.62   464.4 2586.52
   472.9 2583.55   485.7 2582.67     496 2583.57     507 2585.87   519.8 2591.92
   549.7 2592.93   626.5 2589.21   682.4 2611.59   706.9 2629.26   729.6 2630.61
   735.2 2633.13   746.6 2645.01   819.6  2682.3   835.5 2687.99   856.8 2700.42
#Mann= 3 ,-1,0
       0      .1       0   472.9    .045       0     496      .1       0
Bank Sta=472.9,496
XS Rating Curve= 0 ,0
Exp/Cntr(USF)=0,0
Exp/Cntr=0.3,0.1

Type RM Length L Ch R = 1 ,15165   ,475.1,477.4,475.7
XS GIS Cut Line= 3
2230960.94491185 629676.96581671 2231236.5063883629323.493527296
2231450.24188203629024.148671938
#Sta/Elev= 30
       0 2655.24     5.3 2652.78    30.2 2649.21    50.4 2639.16    89.8 2626.87
   212.7 2604.79   263.5 2598.52   334.5  2597.3   344.2 2592.67   358.4 2578.73
     367 2576.48     370 2576.25  390.832576.536   402.1 2579.88   412.6 2581.13
   475.2 2583.42   539.5 2581.39   587.3 2582.46   599.1 2587.01   613.1 2596.13
   641.7 2622.56   661.8 2624.03   664.7 2625.73   667.3 2628.33   677.1 2642.63
     702 2651.81   750.5 2674.26   759.3 2676.55   767.9 2680.98     816 2698.75
#Mann= 3 ,-1,0
       0      .1       0     367    .045       0  390.83      .1       0
Bank Sta=367,390.83
XS Rating Curve= 0 ,0
Exp/Cntr=0.3,0.1

Type RM Length L Ch R = 1 ,14688   ,506.3,506.1,504.6
XS GIS Cut Line= 2
 2231283.0067965629876.6285374112231818.42117476629284.788756293
#Sta/Elev= 30
       0 2643.71   103.1 2607.84   147.7 2597.77   161.1 2596.91   198.5 2587.73
   235.5 2583.29   264.1 2571.54   274.3 2569.61   306.3 2570.82   371.4  2568.5
   414.6 2570.04   439.4 2567.38   459.2 2569.09   493.2 2565.69   508.5 2565.37
  514.912565.722   527.9 2573.42   544.3 2587.64   569.7 2588.43   592.3 2604.77
   603.9 2616.44   627.8 2626.72   641.1  2628.8   662.7 2639.56   677.3 2641.82
   691.4 2650.48     722 2663.24   735.1 2665.91   765.2 2680.45   798.1 2691.11
#Mann= 3 ,-1,0
       0      .1       0   493.2    .045       0  514.91      .1       0
#XS Ineff= 2 , 0
          398.56 2586.55
Permanent Ineff=
       F       F
Bank Sta=493.2,514.91
XS Rating Curve= 0 ,0
Exp/Cntr(USF)=0,0
Exp/Cntr=0.3,0.1

Type RM Length L Ch R = 1 ,14181   ,164.1,158.6,154.2
BEGIN DESCRIPTION:
Structure XS 4
END DESCRIPTION:
XS GIS Cut Line= 2
2231700.55477767630141.2009819362232165.75087681629540.583915929
#Sta/Elev= 30
       0 2637.33    35.4 2623.72    68.2 2614.83   116.4 2605.53   151.8  2595.5
   242.9 2579.24   283.4 2567.05   328.9 2561.53   345.6 2556.28   367.5 2558.23
   381.8 2556.69   407.5 2558.19   444.5 2555.52   453.9 2553.64   465.5 2552.58
   473.42553.608   501.6 2559.96   518.7  2559.1   538.6 2561.39   571.7 2581.22
   575.7 2585.46   584.2 2598.08   602.1  2611.3   607.2 2613.41   622.3 2615.79
   638.4 2625.46   672.9 2640.45   708.4 2651.95   723.9 2659.07   759.7 2671.75
#Mann= 3 ,-1,0
       0      .1       0   453.9    .045       0   473.4      .1       0
#XS Ineff= 2 , 0
          401.44 2577.41
Permanent Ineff=
       F       F
Bank Sta=453.9,473.4
XS Rating Curve= 0 ,0
Exp/Cntr(USF)=0,0
Exp/Cntr=0.3,0.1

Type RM Length L Ch R = 1 ,14023   ,64,64.8,62
BEGIN DESCRIPTION:
Structure XS 3
END DESCRIPTION:
XS GIS Cut Line= 4
2231858.53439191630237.2224329672232084.69500595629955.724647396
2232107.55166376 629787.307168852232229.05284471629586.409176583
#Sta/Elev= 30
       0 2635.72    18.3 2629.74    29.6 2624.18    41.1 2622.76   210.4 2571.88
   225.8    2566   258.1 2558.56   274.3 2555.71   288.6 2555.38   302.8 2551.25
   339.8  2553.3   367.7  2551.5   387.9 2553.77   408.1 2551.99   418.22547.602
   432.3 2546.67  438.772547.525   468.6 2552.96   508.6 2554.61   542.9 2558.45
   552.2  2565.1   561.6 2568.14   589.6 2584.73   626.3  2607.9   641.1 2614.32
   655.4  2623.4   659.8 2625.17   673.8  2626.4   699.1 2637.81   765.8 2662.53
#Mann= 3 ,-1,0
       0      .1       0   418.2    .045       0  438.77      .1       0
Bank Sta=418.2,438.77
XS Rating Curve= 0 ,0
Exp/Cntr(USF)=0,0
Exp/Cntr=0.3,0.1

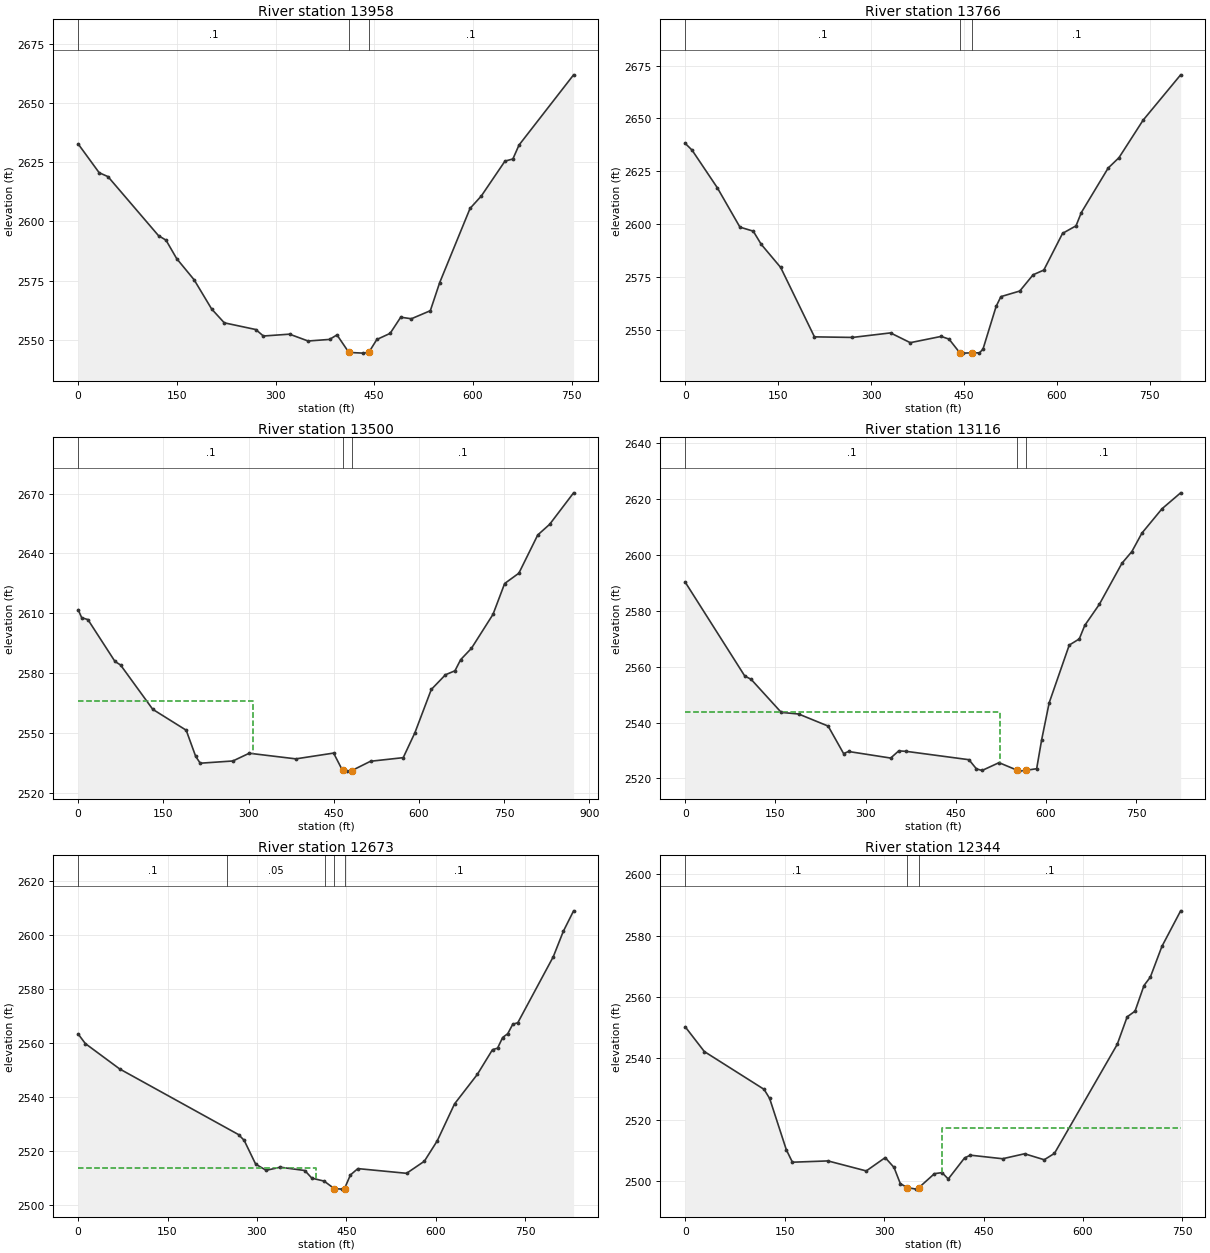
Type RM Length L Ch R = 1 ,13958   ,187.9,192.5,200.9
BEGIN DESCRIPTION:
Structure XS 2
END DESCRIPTION:
XS GIS Cut Line= 4
 2231905.4506895630254.0641808222232146.04708742629953.318683417
2232166.49778125629808.9608446632232279.57808827629617.686708313
#Sta/Elev= 30
       0  2632.8    31.9 2620.63    45.3 2618.98   122.1 2594.01   133.5 2592.11
   149.7 2584.31   176.2 2575.36   202.9 2562.98   222.1 2557.14     270  2554.3
   281.5 2551.56   321.3 2552.34   349.5 2549.45   382.1 2550.12   393.4 2552.03
  411.472544.614   433.2 2544.32   441.8 2544.65     454 2550.09   474.2 2552.68
   490.3 2559.51   506.5 2558.86   535.3 2562.26   549.5 2574.12   595.7 2605.53
   612.8 2610.78   648.8 2625.55   660.8 2626.44   670.1 2632.32   753.1 2662.04
#Mann= 3 ,-1,0
       0      .1       0  411.47    .045       0   441.8      .1       0
Bank Sta=411.47,441.8
XS Rating Curve= 0 ,0
Exp/Cntr(USF)=0,0
Exp/Cntr=0.3,0.1

Type RM Length L Ch R = 1 ,13766   ,276.5,265.8,262.4
BEGIN DESCRIPTION:
Structure XS 1
END DESCRIPTION:
XS GIS Cut Line= 3
2232057.82119001  630370.1065871 2232355.6713986629958.794565514
 2232467.6726993629689.144133784
#Sta/Elev= 30
       0 2638.21      11 2635.04    51.8 2617.25    88.3 2598.64   109.8 2596.74
   122.7  2590.5   154.1 2579.57   208.6 2546.78     270 2546.51   331.4 2548.65
   363.3 2544.03   413.2 2546.99   425.9 2545.71   443.12539.316   449.2 2539.09
   462.82539.237     475 2539.22   480.7 2540.98   501.9 2561.17   509.6 2565.79
   540.1 2568.44   561.6 2576.12   578.9 2578.34   609.2  2595.7   630.9 2599.25
   639.5 2605.55   682.8 2626.57   700.2 2631.45   739.1 2649.15   799.8 2670.62
#Mann= 3 ,-1,0
       0      .1       0   443.1    .045       0   462.8      .1       0
Bank Sta=443.1,462.8
XS Rating Curve= 0 ,0
Exp/Cntr=0.3,0.1

Type RM Length L Ch R = 1 ,13500   ,379.7,384,387.8
XS GIS Cut Line= 4
2232514.33447671630546.2099846932232618.40799754630398.250039413
2232519.35006807629976.9403647192232592.07614287629728.668592131
#Sta/Elev= 30
       0 2611.77     6.2 2607.79    17.1 2606.86    64.8 2585.85    74.6 2584.09
   131.3 2561.85   190.2 2551.37   206.9 2538.26   214.9 2534.82   272.4 2535.94
   301.2 2539.82   383.3    2537   449.8  2539.9   465.5 2531.19   473.7 2530.85
     482 2531.15   514.8  2535.8   572.4 2537.61     593 2550.14   621.8  2571.8
   646.8 2579.19   663.5 2581.18   673.5 2586.75   692.6 2592.48   730.5 2609.49
     751 2624.95     776 2630.11   809.3 2649.31   830.2 2654.62   872.4 2670.43
#Mann= 3 ,-1,0
       0      .1       0   465.5    .045       0     482      .1       0
#XS Ineff= 2 , 0
          307.86 2565.96
Permanent Ineff=
       F       F
Bank Sta=465.5,482
XS Rating Curve= 0 ,0
Exp/Cntr(USF)=0,0
Exp/Cntr=0.3,0.1

Type RM Length L Ch R = 1 ,13116   ,439.8,443.1,448
XS GIS Cut Line= 3
2232694.78878564630581.7623222892232815.58660291630357.545525097
2232976.42525326629811.396821534
#Sta/Elev= 30
       0 2590.28    98.9 2556.72   109.7 2555.47   159.7 2543.65   188.5 2543.08
   237.7 2538.75   263.4 2528.91   271.7 2529.65   341.7  2527.3   355.1 2529.87
   367.7  2529.7   471.9 2526.71   484.4 2523.41   493.8 2522.86   521.9 2525.65
  552.522522.913   555.3 2522.62   567.6 2522.94   584.5 2523.48   592.8 2533.82
   605.3 2547.06   638.7 2567.76   655.4 2569.96   664.5  2574.8   688.7 2582.33
   726.3 2597.03   742.9 2601.26   759.6 2607.86     793 2616.57     824 2622.28
#Mann= 3 ,-1,0
       0      .1       0  552.52    .045       0   567.6      .1       0
#XS Ineff= 2 , 0
          522.92 2543.94
Permanent Ineff=
       F       F
Bank Sta=552.52,567.6
XS Rating Curve= 0 ,0
Exp/Cntr=0.3,0.1

Type RM Length L Ch R = 1 ,12673   ,329.8,329.1,326.8
XS GIS Cut Line= 4
 2232994.8311885 630655.484027362233147.55288659630403.265630779
 2233357.5420374 630208.934871992233441.88756551629973.039553966
#Sta/Elev= 30
       0 2563.43      12 2559.89    69.6  2550.5   269.2 2526.17   278.6 2524.04
   297.9 2515.23   315.6 2512.94   339.1  2514.1   380.4 2512.87   392.2 2510.04
   412.8 2508.95   429.8 2506.16   442.9 2505.98  447.012506.176   456.9 2511.23
   469.4 2513.58   551.2 2511.84     581 2516.31   602.7 2523.89   631.7 2537.56
   669.9 2548.47   695.4 2557.64   703.9 2558.19   712.4 2562.14   720.9 2563.53
   729.4 2567.04   737.9 2567.63   797.4 2592.06   814.3 2601.49   831.5 2609.06
#Mann= 5 ,-1,0
       0      .1       0     250     .05       0  414.85      .1       0
   429.8    .045       0  447.01      .1       0
#XS Ineff= 2 , 0
          399.41 2513.75
Permanent Ineff=
       F       F
Bank Sta=429.8,447.01
XS Rating Curve= 0 ,0
Exp/Cntr=0.3,0.1

Type RM Length L Ch R = 1 ,12344   ,290.3,291.4,294.1
XS GIS Cut Line= 4
 2233356.9538261630798.2434508052233405.85584191630647.775709842
2233646.60422745630328.031760298 2233733.1231785630160.009449556
#Sta/Elev= 30
       0 2550.25    28.8  2542.2   118.9 2529.89   127.3 2526.94   152.5 2510.21
   161.7 2506.15   215.3 2506.57   273.1 2503.31   301.7 2507.65     315 2504.44
   324.5 2499.17     335 2497.88   348.3 2497.38  352.572497.892     376 2502.42
   387.4 2502.76   396.8 2500.68   421.4 2507.54   430.2 2508.44   478.8 2507.28
     512  2508.9   541.6 2506.95     557 2509.02   651.7 2544.52   666.7  2553.5
   678.6 2555.36   692.1 2563.71   701.7 2566.46   719.1 2576.44   747.4 2588.04
#Mann= 3 ,-1,0
       0      .1       0     335    .045       0  352.57      .1       0
#XS Ineff= 2 , 0
                          387.58         2517.45
Permanent Ineff=
       F       F
Bank Sta=335,352.57
XS Rating Curve= 0 ,0
Exp/Cntr(USF)=0,0
Exp/Cntr=0.3,0.1

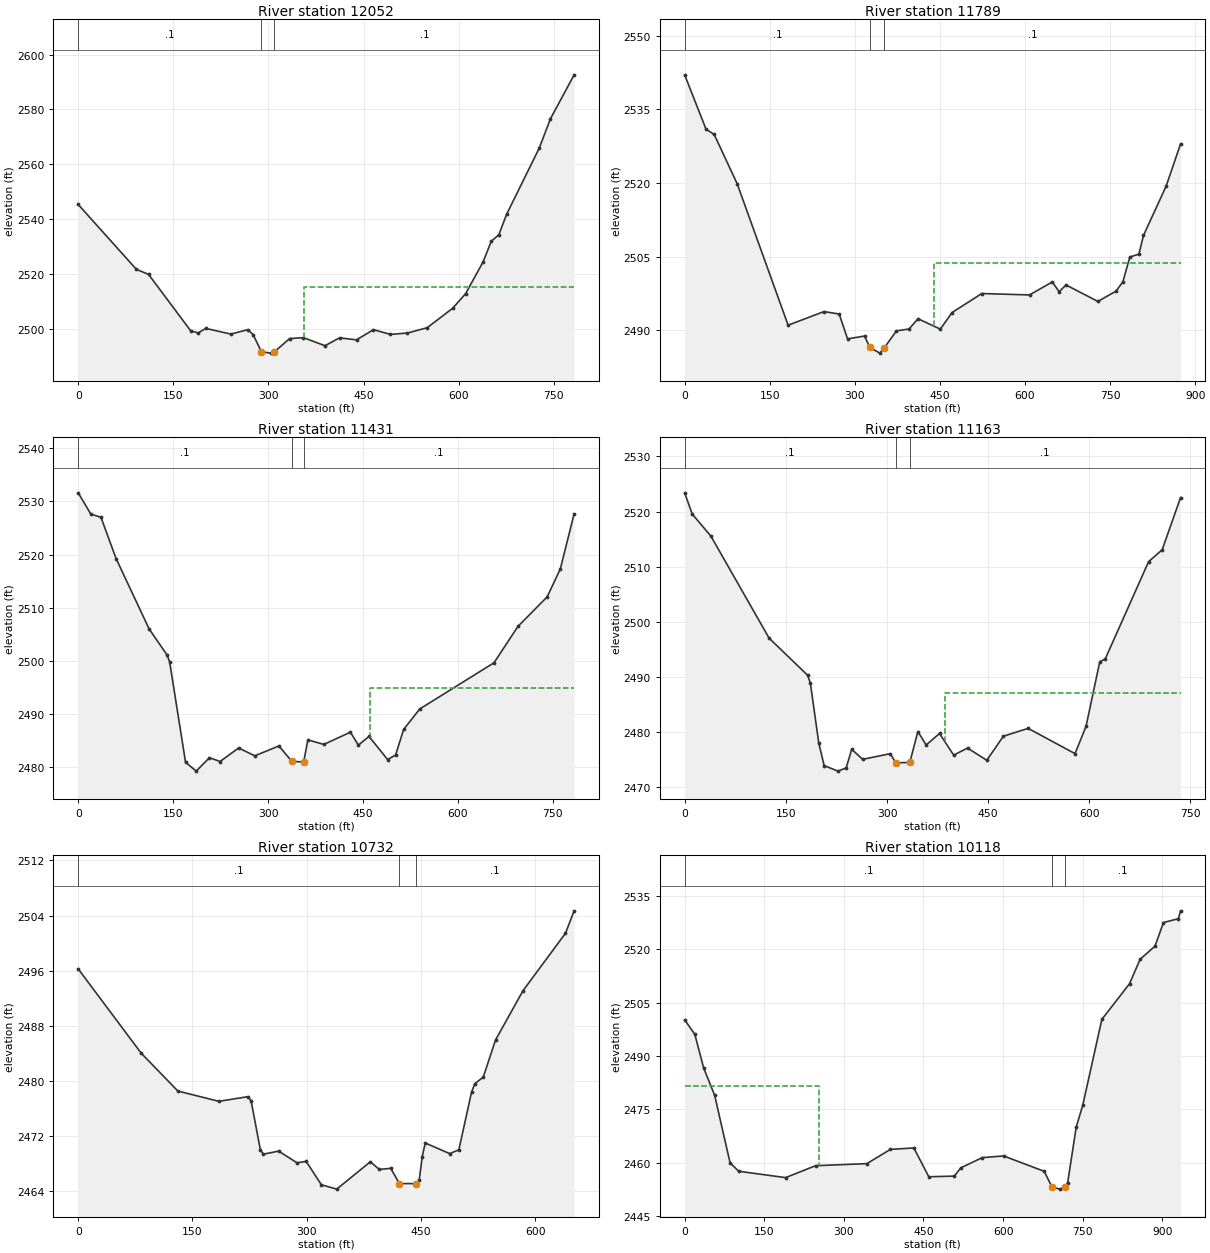
Type RM Length L Ch R = 1 ,12052   ,256.8,263.8,264.5
XS GIS Cut Line= 3
2233512.43715842630891.031891064 2233914.9383655630532.417108438
2233948.79360721630291.668722898
#Sta/Elev= 30
       0 2545.29    91.8 2521.62     111 2519.79   177.2 2499.27   189.2 2498.42
   201.2 2500.08   240.7    2498   267.5 2499.62   275.9 2497.84   288.9 2491.58
   303.4 2491.06   309.4 2491.53   333.5 2496.38   355.3  2496.7   389.3 2493.76
   412.2 2496.64     439  2495.9   465.7 2499.62   492.5 2497.89   519.3 2498.39
   550.4 2500.33   590.8 2507.46     611 2512.75   638.7 2524.38   651.4 2531.83
   663.5 2534.27   675.7  2541.7   727.2 2565.87   744.9 2576.59   782.2  2592.6
#Mann= 3 ,-1,0
       0      .1       0   288.9    .045       0   309.4      .1       0
#XS Ineff= 2 , 0
                          356.39         2515.17
Permanent Ineff=
       F       F
Bank Sta=288.9,309.4
XS Rating Curve= 0 ,0
Exp/Cntr(USF)=0,0
Exp/Cntr=0.3,0.1

Type RM Length L Ch R = 1 ,11789   ,354.7,357.8,359
XS GIS Cut Line= 3
2233637.82694256631001.3749011032234169.47962729 630729.27906953
2234445.33715239630702.947214862
#Sta/Elev= 30
       0 2542.04    37.6 2530.99    52.1 2529.89    92.5 2519.88   182.4 2491.05
   245.6 2493.82   272.4 2493.33   287.2 2488.26   317.2 2488.84  326.52 2486.51
   344.1 2485.36   352.32486.496   373.4 2489.89   395.5 2490.27   411.5 2492.36
   450.7 2490.25   471.5 2493.63   523.9  2497.5     608 2497.21   648.2 2499.86
   660.2 2497.85   672.3 2499.25   728.5 2495.89   760.7    2498   772.7 2499.92
   784.8 2504.93   800.9 2505.53   808.9 2509.32   848.9 2519.38   874.3 2527.98
#Mann= 3 ,0,0
       0      .1       0  326.52    .045       0   352.3      .1       0
#XS Ineff= 2 , 0
                          438.99         2503.66
Permanent Ineff=
       F       F
Bank Sta=326.52,352.3
XS Rating Curve= 0 ,0
Exp/Cntr(USF)=0,0
Exp/Cntr=0.3,0.1

Type RM Length L Ch R = 1 ,11431   ,267.4,267.9,269
XS GIS Cut Line= 3
2233724.34589361631249.6466736912233864.78245184 631239.61549096
2234476.68459842631042.753529868
#Sta/Elev= 30
       0  2531.6    19.9 2527.61    35.9 2527.01      60  2519.2   112.1    2506
   140.2 2501.15   144.4 2499.87   169.6 2480.96   186.4 2479.28   207.4  2481.8
   224.2 2481.09   253.5 2483.63     279 2482.16   317.1 2484.01   337.7  2481.1
  356.292481.014   362.9 2485.16   388.1  2484.3   430.1  2486.6   442.7 2484.17
   459.5  2485.8   488.9 2481.45   501.5 2482.31   514.2 2487.11   539.6 2490.96
     657 2499.65   694.8 2506.48     741 2512.04   761.8  2517.3   783.6 2527.64
#Mann= 3 ,-1,0
       0      .1       0   337.7    .045       0  356.29      .1       0
#XS Ineff= 2 , 0
                          460.94         2494.86
Permanent Ineff=
       F       F
Bank Sta=337.7,356.29
XS Rating Curve= 0 ,0
Exp/Cntr(USF)=0,0
Exp/Cntr=0.3,0.1

Type RM Length L Ch R = 1 ,11163   ,429.6,431.1,435.7
XS GIS Cut Line= 4
2233749.04449925631443.1043237972233908.66887629631472.840489452
2234354.83911646631379.1588504032234471.37237124631368.308634538
#Sta/Elev= 30
       0 2523.39    11.3 2519.53    38.8 2515.57   125.2 2497.06   182.3 2490.34
   186.4 2488.91   198.8 2478.08   206.8 2473.97   227.3 2472.96   239.5 2473.55
   247.7 2476.91     264  2475.1   304.9 2476.12   313.1 2474.46  333.83 2474.54
   345.8 2480.13   358.1  2477.7   377.9 2479.78   398.9 2475.86   419.4 2477.14
     448 2474.93   472.6 2479.29   509.3 2480.71   578.8 2476.13   595.1 2481.05
   615.5 2492.78   623.6 2493.29   687.9 2510.92     708 2513.06   735.3 2522.54
#Mann= 3 ,-1,0
       0      .1       0   313.1    .045       0  333.83      .1       0
#XS Ineff= 2 , 0
                          385.85         2487.07
Permanent Ineff=
       F       F
Bank Sta=313.1,333.83
XS Rating Curve= 0 ,0
Exp/Cntr=0.3,0.1

Type RM Length L Ch R = 1 ,10732   ,611.3,613.5,611.2
XS GIS Cut Line= 3
2233765.72452238631810.1390087752234292.36161574631846.502046174
 2234415.2436042631840.232556968
#Sta/Elev= 30
       0 2496.27    82.6 2484.06   130.8 2478.56   184.6 2477.07     223 2477.75
     227 2477.11     239 2470.08     243 2469.41   263.1 2469.85   287.1 2468.16
   299.2 2468.36   319.2 2464.97   339.3 2464.34   383.4  2468.3   395.2 2467.19
   410.2 2467.36   421.5 2465.15   443.5 2465.14   447.5  2465.6   451.6 2469.07
   455.5 2471.03   487.6 2469.49   499.6 2470.04   516.2 2478.37   520.5 2479.62
   531.7 2480.59   547.7 2485.95   583.8 2493.11   639.5 2501.43   650.9 2504.69
#Mann= 3 ,-1,0
       0      .1       0   421.5    .045       0   443.5      .1       0
Bank Sta=421.5,443.5
XS Rating Curve= 0 ,0
Exp/Cntr(USF)=0,0
Exp/Cntr=0.3,0.1

Type RM Length L Ch R = 1 ,10118   ,541.5,546.4,552.7
XS GIS Cut Line= 4
2233633.69738278632258.5088935762233716.82250656632281.604597123
2234402.48366616632359.9844733942234560.26365186632367.486538154
#Sta/Elev= 30
       0 2500.15    19.2 2496.06    35.8 2486.62    56.5 2478.95    85.6 2459.96
   101.7 2457.61   190.1 2455.81   246.7 2459.16   343.3 2459.74   387.6 2463.74
   431.9 2464.15     460 2456.05     508 2456.24   520.4 2458.57   560.7 2461.43
     601  2461.9   677.5 2457.58   692.3 2453.11   706.7 2452.58  716.162453.108
   721.7 2454.43   737.8 2470.01   750.1 2476.15   786.1 2500.28   838.2 2510.27
   858.2 2517.17   886.2 2520.84   902.2 2527.48   930.3 2528.56   934.4 2530.77
#Mann= 3 ,-1,0
       0      .1       0   692.3    .045       0  716.16      .1       0
#XS Ineff= 2 , 0
          253.43 2481.55
Permanent Ineff=
       F       F
Bank Sta=692.3,716.16
XS Rating Curve= 0 ,0
Exp/Cntr=0.3,0.1