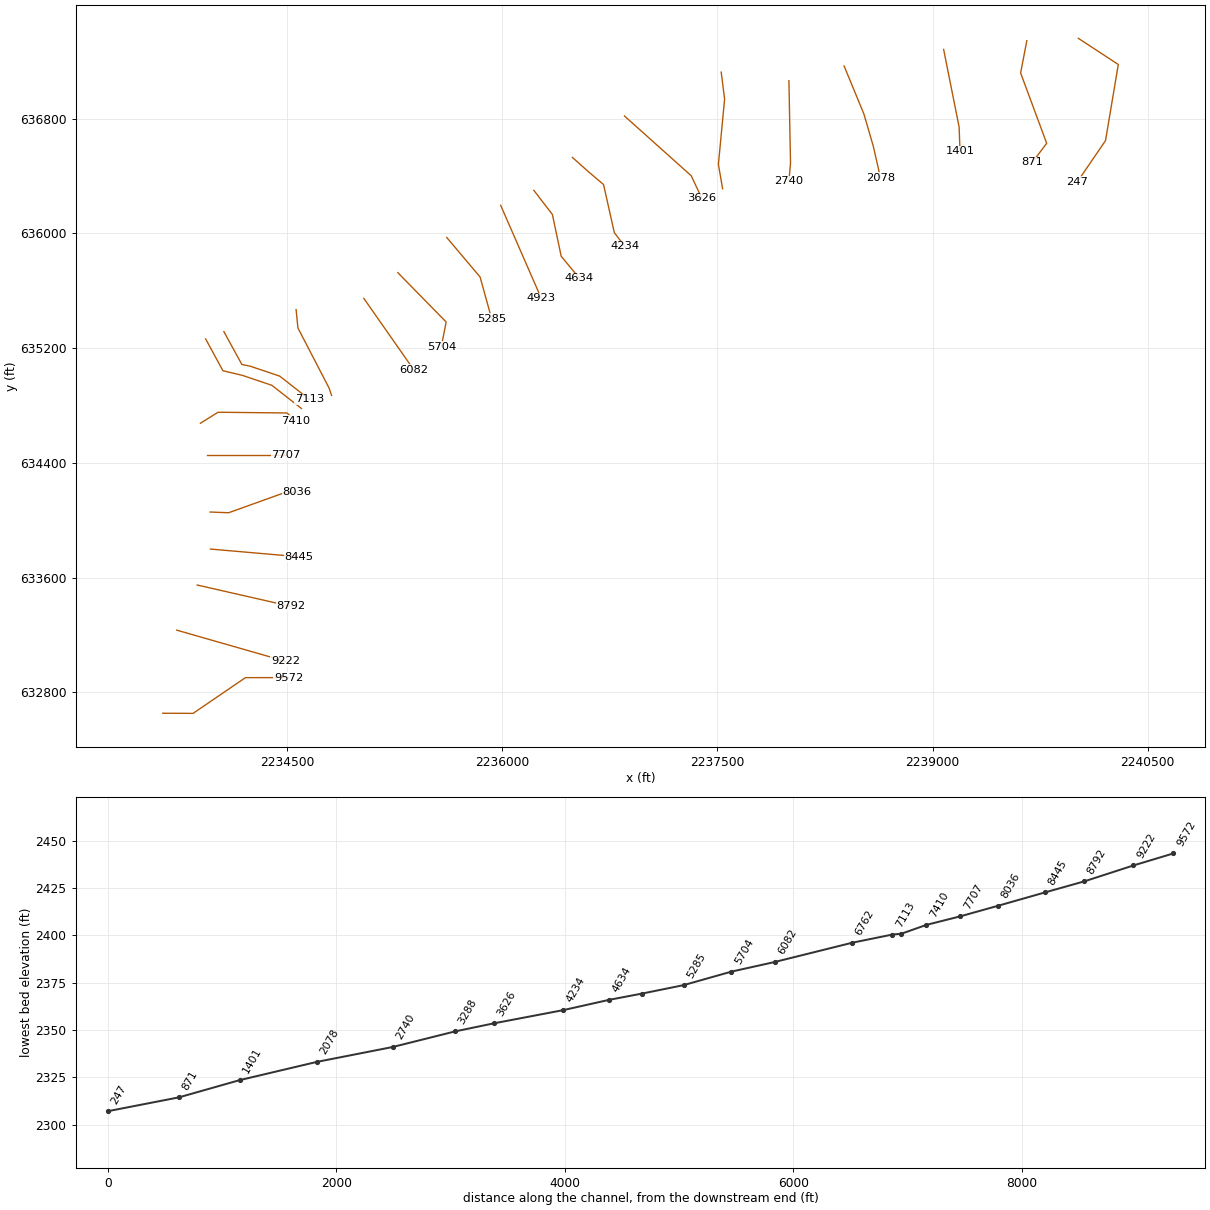
HEC-RAS study BIRCHFK.prj: BIRCHFK

--- BIRCHFK.g01 (geometry) --- (continued)

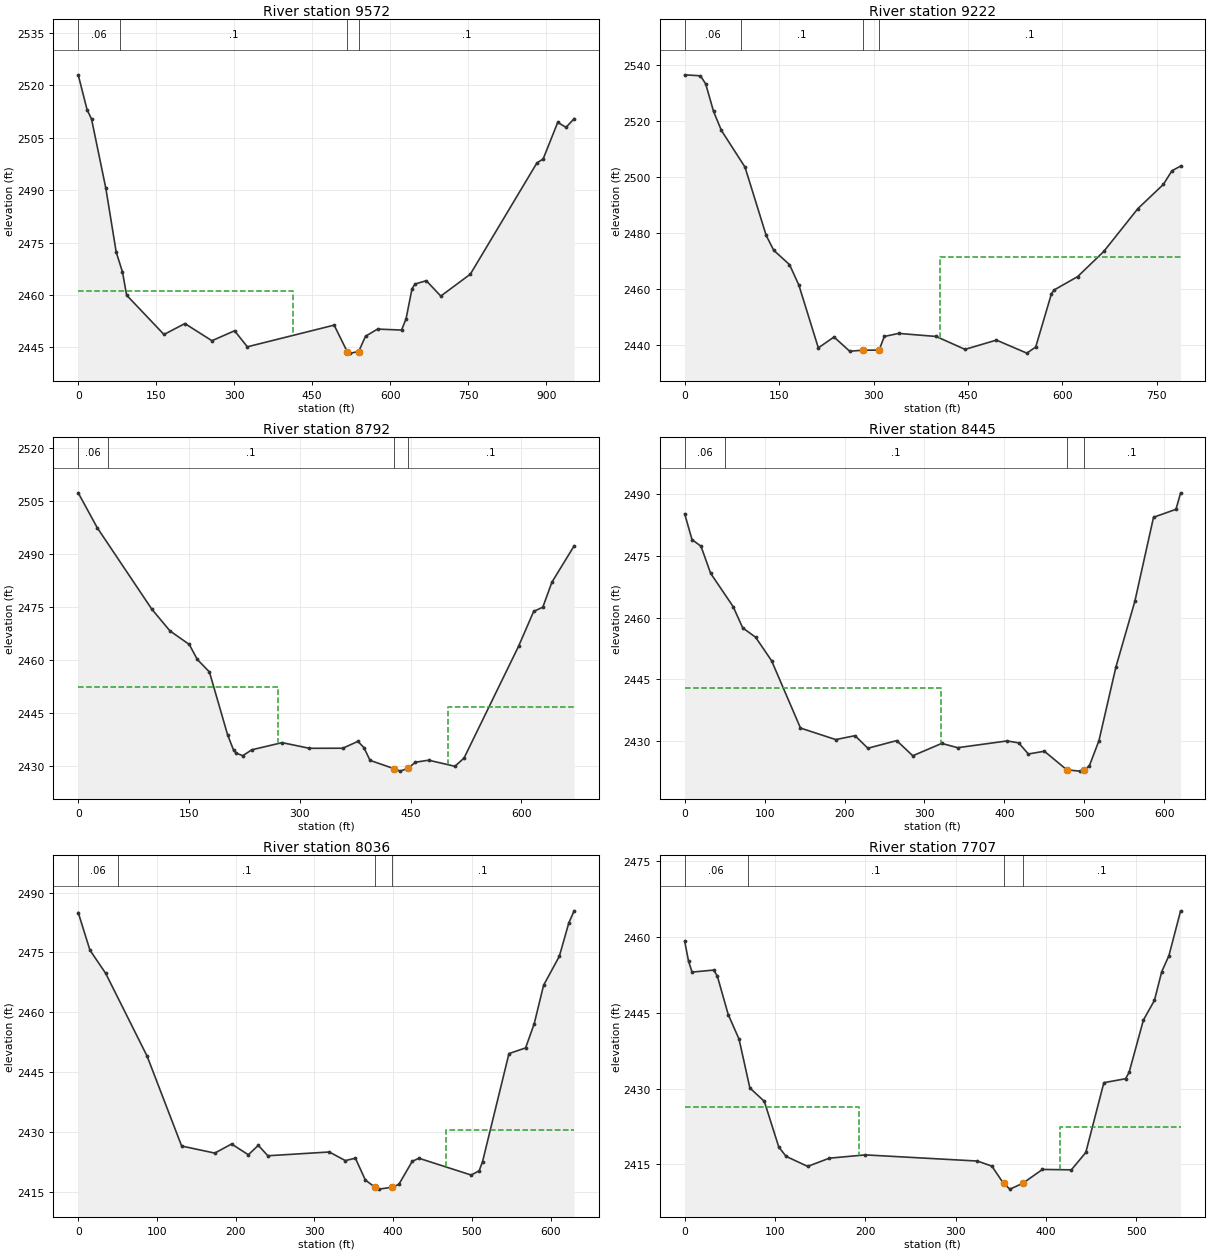
Type RM Length L Ch R = 1 ,9572    ,362.4,350.1,341
XS GIS Cut Line= 4
2233631.02978564 632653.70197264 2233842.2122907632652.758358164
2234207.57162299632901.9167899092234507.72602736632902.214720884
#Sta/Elev= 30
       0    2523    17.1 2512.99    25.6 2510.36    53.1 2490.55    73.1 2472.25
    85.1 2466.62    93.1 2459.97   164.9 2448.72   205.1 2451.85   257.1 2446.94
   300.7 2449.79   325.2  2445.2   492.1  2451.4   517.2 2443.83   523.4 2443.39
  539.192443.827   552.5 2448.23   575.6 2450.27   621.7 2449.99   630.3 2453.15
   641.8 2461.78   647.6 2463.16   669.3 2464.11   697.2 2459.71     754 2465.98
     882  2497.8     894 2498.93     922  2509.4     938 2507.97   953.6 2510.48
#Mann= 4 ,-1,0
       0     .06       0      80      .1       0   517.2    .045       0
  539.19      .1       0
#XS Ineff= 2 , 0
          413.72 2461.21
Permanent Ineff=
       F       F
Bank Sta=517.2,539.19
XS Rating Curve= 0 ,0
Exp/Cntr=0.3,0.1

Type RM Length L Ch R = 1 ,9222    ,431.5,430.1,429
XS GIS Cut Line= 2
2233728.10758714633233.3130587092234485.46188331633016.388732155
#Sta/Elev= 30
       0 2536.39      25 2536.05    33.4 2533.15    45.8 2523.37    58.3 2516.55
    95.8 2503.45   129.5 2479.03   141.5 2473.73   166.5 2468.63   181.3 2461.37
   212.3 2438.89   237.2 2442.78   262.2 2437.69     283 2438.08   308.82438.079
   317.1 2442.97   339.8 2444.06   399.5 2442.97   445.3 2438.36   495.2 2441.67
   543.5 2437.02   557.6  2439.2   582.6 2458.21   586.7 2459.55   624.2 2464.34
   665.8 2473.34   719.9 2488.62   760.3 2497.24     774 2502.13   787.8 2503.81
#Mann= 4 ,-1,0
       0     .06       0      90      .1       0     283    .045       0
   308.8      .1       0
#XS Ineff= 2 , 0
                          404.87         2471.28
Permanent Ineff=
       F       F
Bank Sta=283,308.8
XS Rating Curve= 0 ,0
Exp/Cntr(USF)=0,0
Exp/Cntr=0.3,0.1

Type RM Length L Ch R = 1 ,8792    ,344.4,346.2,347.5
XS GIS Cut Line= 2
2233871.05194105633548.0414168892234525.58661423633398.827573768
#Sta/Elev= 30
       0 2507.35    25.8 2497.46    99.6 2474.44   124.2 2468.28   150.3 2464.45
   161.2  2460.2   177.6 2456.67   202.2 2438.89   210.4 2434.48   213.8 2433.71
   222.7 2432.96     235 2434.64     276 2436.66     313 2435.06   358.1 2435.08
   378.6 2437.02   386.8 2435.24     395 2431.65   426.8 2429.34     436  2428.6
  446.452429.413   456.5 2431.13   474.4 2431.69   509.9 2429.97   522.2 2432.28
     596 2463.91   616.5 2473.79   628.9    2475   641.2 2482.07   671.3 2492.34
#Mann= 4 ,-1,0
       0     .06       0      40      .1       0   426.8    .045       0
  446.45      .1       0
#XS Ineff= 2 , 0
          270.54 2452.27     500         2446.77
Permanent Ineff=
       F       F
Bank Sta=426.8,446.45
XS Rating Curve= 0 ,0
Exp/Cntr(USF)=0,0
Exp/Cntr=0.3,0.1

Type RM Length L Ch R = 1 ,8445    ,404.1,409.6,413.4
XS GIS Cut Line= 2
2233963.84038131633798.820985159 2234582.0120171633744.903377981
#Sta/Elev= 30
       0 2485.19     9.2 2478.94    20.4 2477.33    32.5 2470.75    60.6 2462.68
    72.6 2457.51    88.7 2455.24   108.7 2449.54   144.9 2433.18     189 2430.38
   213.1 2431.33   229.2 2428.28   265.3 2430.13   285.4 2426.45   321.6 2429.45
   341.6 2428.41   403.3 2430.05   417.9 2429.58     430 2426.88     450 2427.55
   478.2 2423.03   494.2 2422.72  499.092423.029   506.2 2423.94   518.3 2430.11
   539.6 2448.05   563.2 2463.93   586.6 2484.36   614.7  2486.3   620.5  2490.3
#Mann= 4 ,-1,0
       0     .06       0      50      .1       0   478.2    .045       0
  499.09      .1       0
#XS Ineff= 2 , 0
          320.16 2442.98
Permanent Ineff=
       F       F
Bank Sta=478.2,499.09
XS Rating Curve= 0 ,0
Exp/Cntr(USF)=0,0
Exp/Cntr=0.3,0.1

Type RM Length L Ch R = 1 ,8036    ,332.7,329.3,326.2
XS GIS Cut Line= 4
2233961.33258563634057.1239404772234090.48406329634052.108349112
2234477.93849626634191.291009502  2234566.965243634193.798805185
#Sta/Elev= 30
       0 2484.99    14.9 2475.56    34.9 2469.74    87.5    2449   131.4 2426.47
   173.5  2424.7   194.8 2426.98   216.1 2424.29   228.8 2426.64   240.9 2424.03
     319 2424.98   339.3 2422.82   352.1 2423.42   364.8 2417.94  377.132416.134
   381.8 2415.67   398.8 2416.14   407.3 2416.86   424.3 2422.63   432.8 2423.41
   499.2  2419.2   509.3 2420.26   513.6 2422.54   547.2 2449.64   568.3 2451.05
   579.2 2457.08   591.2 2466.77   611.2 2474.03   623.2 2482.38     630 2485.41
#Mann= 4 ,-1,0
       0     .06       0      50      .1       0  377.13    .045       0
   398.8      .1       0
#XS Ineff= 2 , 0
                          467.44         2430.57
Permanent Ineff=
       F       F
Bank Sta=377.13,398.8
XS Rating Curve= 0 ,0
Exp/Cntr(USF)=0,0
Exp/Cntr=0.3,0.1

Type RM Length L Ch R = 1 ,7707    ,297,296.8,296.6
XS GIS Cut Line= 2
2233940.01632232634453.3556583442234489.22357684634453.355658344
#Sta/Elev= 30
       0  2459.2     4.3 2455.22     8.2 2453.08    32.2 2453.48    36.2 2452.26
    48.2 2444.68    60.2 2439.81    72.2 2430.13    88.2 2427.49   104.2 2418.44
   112.3 2416.59   136.2  2414.6   160.2 2416.23   200.2 2416.88   324.2 2415.66
   340.2 2414.65  353.122411.217   360.2  2410.1  374.382411.253   396.2    2414
   428.2 2413.92   444.2 2417.36   464.2 2431.18   488.2 2431.96   492.2 2433.25
     508 2443.59   520.2 2447.47   528.3 2453.17   536.2 2456.31   549.2 2465.21
#Mann= 4 ,-1,0
       0     .06       0      70      .1       0  353.12    .045       0
  374.38      .1       0
#XS Ineff= 2 , 0
          192.69 2426.38  415.66         2422.49
Permanent Ineff=
       F       F
Bank Sta=353.12,374.38
XS Rating Curve= 0 ,0
Exp/Cntr(USF)=0,0
Exp/Cntr=0.3,0.1

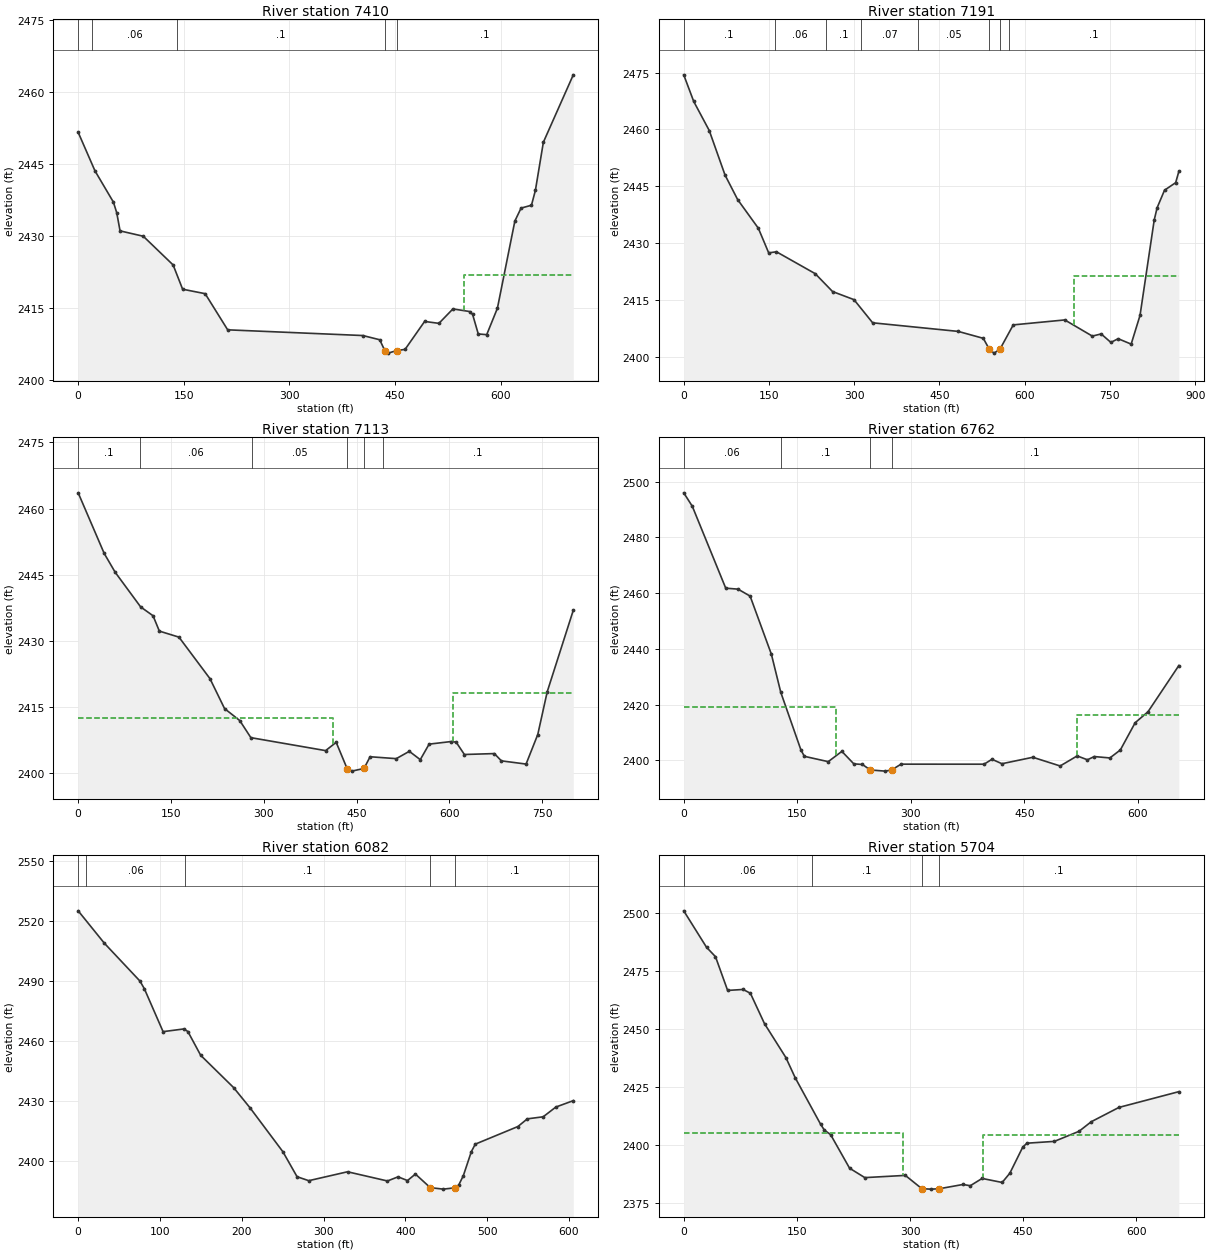
Type RM Length L Ch R = 1 ,7410    ,219.9,218.3,214.2
BEGIN DESCRIPTION:
Structure XS 4
END DESCRIPTION:
XS GIS Cut Line= 4
2233893.62210219634676.5494741052234016.50409065634753.037242428
2234498.00086173634748.0216510622234554.42626459634695.357941725
#Sta/Elev= 30
       0 2451.63    23.9 2443.58    50.1 2437.06    54.8 2434.84    59.5 2431.07
    92.5 2429.95   134.9 2423.96   148.4  2418.9   180.4 2417.97   212.4 2410.43
   404.4 2409.24   428.4 2408.36   435.6 2406.11   440.4 2405.57   452.4  2406.1
   464.4 2406.35   492.2 2412.18   512.5 2411.78   532.4 2414.79   556.4 2414.24
   560.4 2413.63   568.4 2409.57   580.4 2409.42   595.6 2414.93   620.4 2433.12
   629.2 2435.82     644 2436.42   649.6 2439.54   660.9 2449.56   703.4 2463.62
#Mann= 5 ,-1,0
       0      .1       0      20     .06       0     140      .1       0
   435.6    .045       0   452.4      .1       0
#XS Ineff= 2 , 0
                           548.2         2421.97
Permanent Ineff=
       F       F
Bank Sta=435.6,452.4
XS Rating Curve= 0 ,0
Exp/Cntr(USF)=0,0
Exp/Cntr=0.3,0.1

Type RM Length L Ch R = 1 ,7191    ,78.2,78.2,78.7
BEGIN DESCRIPTION:
Structure XS 3
END DESCRIPTION:
XS GIS Cut Line= 5
2233929.98513959635264.6275616992234050.35933236 635042.68764378
2234187.03419707635010.0862999052234391.41954521 634941.12191863
2234598.31268903634779.369097096
#Sta/Elev= 30
       0 2474.43    17.6 2467.39    44.9 2459.72    72.7 2447.95    94.9 2441.47
   131.3  2433.9   149.5  2427.4   163.2 2427.68   231.4  2421.9   261.9 2417.18
   299.6 2415.04   332.5 2408.92     483 2406.65   527.2 2404.82   537.7 2401.94
   546.1 2400.91  556.382401.919   579.9 2408.37   670.6 2409.68     719 2405.41
   734.6 2405.98   751.7 2403.74   764.5 2404.72   787.4 2403.29     803 2410.88
     828 2436.11   833.1 2439.32   846.1 2443.95   865.7 2445.94   871.3  2448.9
#Mann= 8 ,-1,0
       0      .1       0     160     .06       0     250      .1       0
  312.48     .07       0  412.99     .05       0   537.7    .045       0
  556.38     .05       0  572.99      .1       0
#XS Ineff= 2 , 0
                          686.64         2421.38
Permanent Ineff=
       F       F
Bank Sta=537.7,556.38
XS Rating Curve= 0 ,0
Exp/Cntr(USF)=0,0
Exp/Cntr=0.3,0.1

Type RM Length L Ch R = 1 ,7113    ,359.9,351.7,338.7
BEGIN DESCRIPTION:
Structure XS 2
END DESCRIPTION:
XS GIS Cut Line= 5
2234057.16799764635315.3101124462234182.62047667635086.260593767
2234242.10539026635073.972394922 2234446.4907384635005.008013647
2234653.38388222634843.255192113
#Sta/Elev= 30
       0 2463.58    42.1 2449.83    59.8 2445.57     101 2437.71     121 2435.71
   131.2 2432.23   162.9 2430.86     213 2421.45   236.6 2414.66   261.2 2411.94
   279.1 2408.07   399.9 2405.13     417 2407.01   434.6 2401.07   442.3 2400.48
     462 2401.09   471.8 2403.74   514.1 2403.31   535.2 2404.97   552.9 2403.08
   567.2  2406.6   602.3 2407.18   610.8 2407.07   624.2 2404.25   672.6 2404.46
     684 2402.81   723.9 2402.08   742.8 2408.78   758.1 2418.49   800.2 2436.95
#Mann= 6 ,-1,0
       0      .1       0     100     .06       0  281.16     .05       0
   434.6    .045       0     462     .05       0   491.9      .1       0
#XS Ineff= 2 , 0
          412.64 2412.54  605.05         2418.22
Permanent Ineff=
       F       F
Bank Sta=434.6,462
XS Rating Curve= 0 ,0
Exp/Cntr(USF)=0,0
Exp/Cntr=0.3,0.1

Type RM Length L Ch R = 1 ,6762    ,677.4,679.3,682.9
BEGIN DESCRIPTION:
Structure XS 1
END DESCRIPTION:
XS GIS Cut Line= 4
 2234560.9911164635468.4207914142234573.69170831635340.854797915
2234789.89574021634923.8473860362234808.29460121634870.772676851
#Sta/Elev= 30
       0 2496.02    11.3 2491.21    55.5  2461.8    71.7 2461.46    87.7 2458.96
   115.8  2438.1   128.2 2424.44   154.9  2403.7   159.4 2401.46   190.9 2399.55
   208.9 2403.24   224.7 2398.76     236 2398.54   246.6 2396.56   266.3 2396.15
   274.62396.563   287.1 2398.65   396.8 2398.64   407.2  2400.4   420.4 2398.81
   461.2 2401.12   497.3    2398   519.8 2401.61   533.3 2400.22   542.4 2401.38
     563 2400.88   576.8 2403.74   596.4 2413.52   613.4 2417.47   654.1 2434.04
#Mann= 4 ,-1,0
       0     .06       0   128.2      .1       0   246.6    .045       0
   274.6      .1       0
#XS Ineff= 2 , 0
          201.16 2419.31  519.06         2416.21
Permanent Ineff=
       F       F
Bank Sta=246.6,274.6
XS Rating Curve= 0 ,0
Exp/Cntr(USF)=0,0
Exp/Cntr=0.3,0.1

Type RM Length L Ch R = 1 ,6082    ,375.8,378,382.9
XS GIS Cut Line= 2
2235033.45425014635547.0513318262235380.36598624 635051.06507458
#Sta/Elev= 30
       0 2524.95      32 2508.78    75.5 2489.88    80.9 2486.05   103.8  2464.6
   129.2 2465.95   134.1 2464.67   149.8 2452.78     190 2436.67   210.1 2426.56
   250.3  2404.6   267.6 2392.14   281.9 2390.16   329.3 2394.61   378.1 2390.01
   391.1 2392.08   402.6 2390.22   412.3 2393.46   430.5 2386.67   446.5 2385.94
   461.1 2386.62   465.4 2388.12   470.9 2392.68   480.7 2404.69   485.5 2408.41
   537.6 2417.21   549.1 2421.04   568.5 2422.07     584 2426.94   605.3 2430.13
#Mann= 5 ,-1,0
       0      .1       0      10     .06       0     130      .1       0
   430.5    .045       0   461.1      .1       0
Bank Sta=430.5,461.1
XS Rating Curve= 0 ,0
Exp/Cntr(USF)=0,0
Exp/Cntr=0.3,0.1

Type RM Length L Ch R = 1 ,5704    ,417.6,418.8,416.8
XS GIS Cut Line= 3
2235270.30162017635726.7766890862235607.46081751635382.651392626
2235574.02354174635211.285354308
#Sta/Elev= 30
       0 2500.81    30.2 2485.11    42.1 2481.04    58.2  2466.5    78.8 2466.92
    88.4 2465.26   107.1 2452.17   135.4 2437.58   147.8 2428.85   181.4 2408.87
   186.3 2406.37   194.8 2404.31   219.9 2389.87   240.1 2385.82   293.8 2386.78
   315.8 2381.02   327.7 2380.86   338.2 2380.99   370.2 2382.86   379.9 2382.33
   395.6 2385.47   422.2 2383.73   432.4 2387.75   449.4 2398.93     455 2400.66
   491.4 2401.44     524 2405.77   540.3 2409.91     577 2416.08   656.4 2422.87
#Mann= 4 ,-1,0
       0     .06       0     170      .1       0   315.8    .045       0
   338.2      .1       0
#XS Ineff= 2 , 0
          290.61 2404.86  397.26         2404.38
Permanent Ineff=
       F       F
Bank Sta=315.8,338.2
XS Rating Curve= 0 ,0
Exp/Cntr(USF)=0,0
Exp/Cntr=0.3,0.1

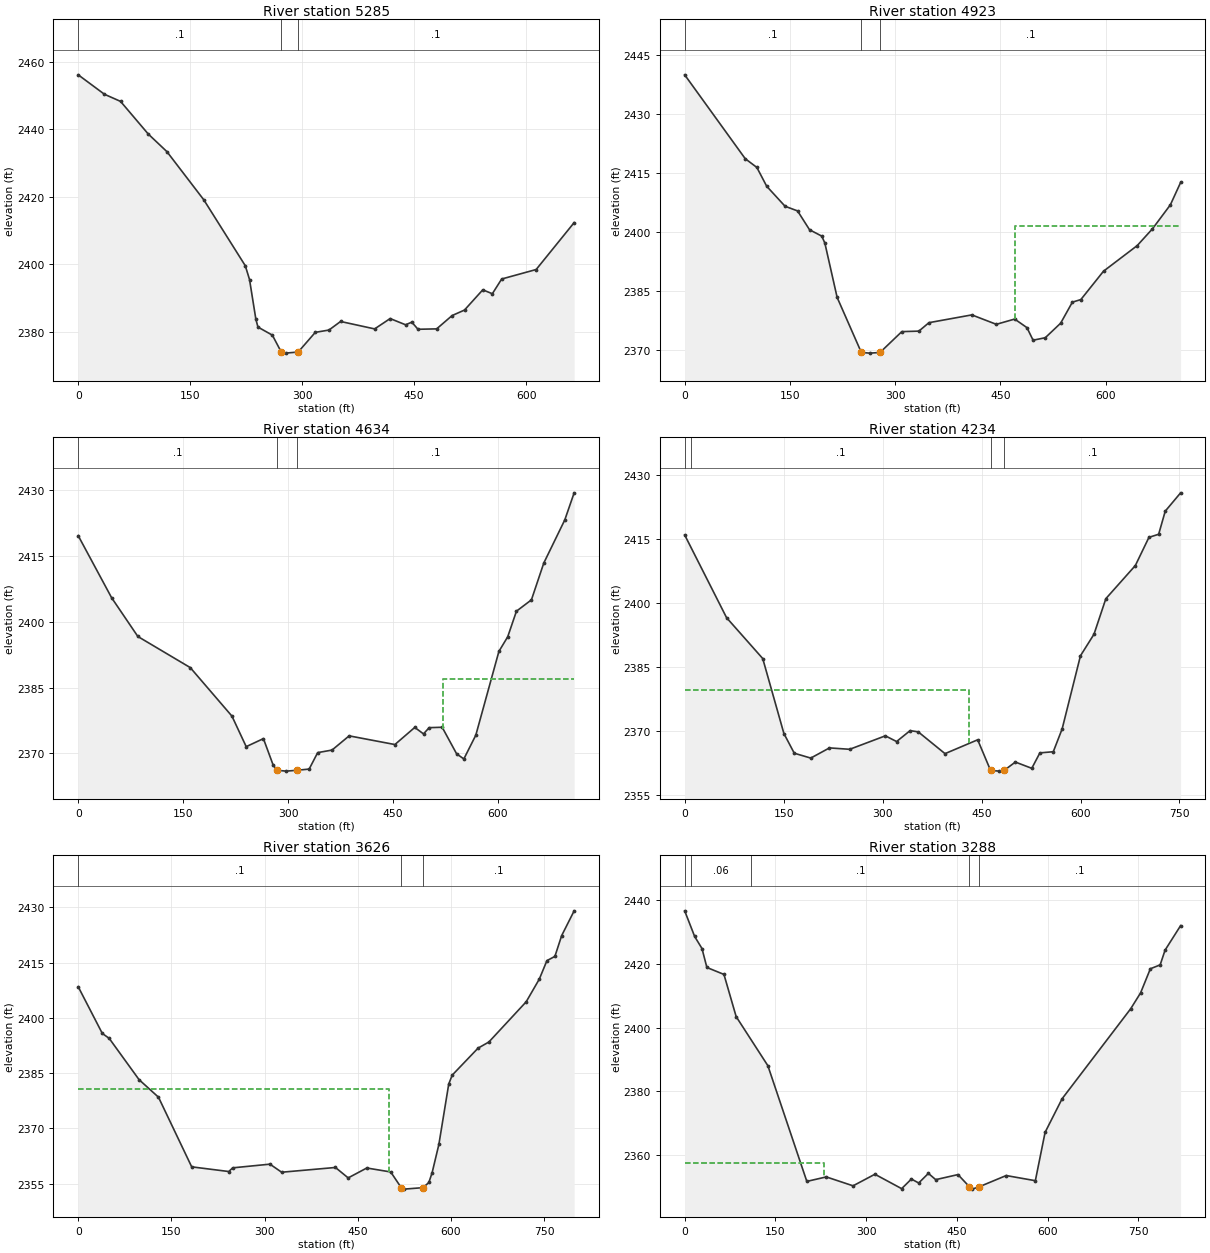
Type RM Length L Ch R = 1 ,5285    ,365.4,362.4,358.2
XS GIS Cut Line= 3
2235611.64047698635971.9833780622235844.30818754635696.125852964
2235925.11493732635403.549689982
#Sta/Elev= 30
       0 2456.09    35.1 2450.34    56.7 2448.23    93.9 2438.55   118.8 2433.36
   168.3 2419.07   223.8 2399.59   229.5  2395.5     238 2383.75   240.8 2381.42
   260.1 2379.03     272 2374.04   277.7 2373.71   294.7 2374.04   317.6 2379.86
   335.9 2380.54   351.5 2383.08   397.1 2380.88   417.9 2383.94   438.6  2382.1
   446.9 2382.88   455.2 2380.77   480.2 2380.89   500.9 2384.83   517.5 2386.46
     542 2392.45   554.8 2391.29   567.3 2395.65   613.5 2398.46   664.4 2412.35
#Mann= 3 ,-1,0
       0      .1       0     272    .045       0   294.7      .1       0
Bank Sta=272,294.7
XS Rating Curve= 0 ,0
Exp/Cntr(USF)=0,0
Exp/Cntr=0.3,0.1

Type RM Length L Ch R = 1 ,4923    ,291.5,288.8,285.8
XS GIS Cut Line= 2
2235987.80982939636196.291769682 2236270.6334536 635548.44455165
#Sta/Elev= 30
       0 2440.08    86.3 2418.74   102.9 2416.51   116.9 2411.73   143.1 2406.63
   160.9 2405.45     178 2400.65   195.4 2399.04   199.8 2397.27   217.3 2383.44
   251.8 2369.43   263.9 2369.26   278.4 2369.42   309.5 2374.73   333.8 2374.86
   348.2 2377.01   409.3 2378.99   444.2 2376.59   470.4 2377.93   487.9 2375.74
   496.6 2372.55     514 2373.18   535.9 2376.88   552.6 2382.23   564.7 2382.89
     597 2390.11     645 2396.62   666.8  2400.9   692.3    2407   706.9 2412.69
#Mann= 3 ,-1,0
       0      .1       0   251.8    .045       0   278.4      .1       0
#XS Ineff= 2 , 0
                          470.76         2401.59
Permanent Ineff=
       F       F
Bank Sta=251.8,278.4
XS Rating Curve= 0 ,0
Exp/Cntr(USF)=0,0
Exp/Cntr=0.3,0.1

Type RM Length L Ch R = 1 ,4634    ,399.7,400.4,400.5
XS GIS Cut Line= 4
2236219.08432013636300.7832564612236348.65376373 636132.20365779
2236409.95543598635841.0207146322236536.73843994635687.766534022
#Sta/Elev= 30
       0 2419.61    47.7 2405.48    85.3 2396.63   160.2 2389.54   219.8 2378.48
   240.2 2371.52   264.8 2373.35   278.9 2367.25   284.5 2366.13   297.5 2365.94
   312.7 2366.13   330.2 2366.41   342.4 2370.16   362.9 2370.74   387.4 2373.98
   452.8    2372   481.2  2375.9   493.7 2374.43   501.8 2375.85   520.4 2375.94
   541.1 2369.87   551.4 2368.72   568.5 2374.14   601.5 2393.23   614.1 2396.56
   626.6  2402.4     648 2404.98   665.7 2413.38   695.7  2423.2   709.1 2429.38
#Mann= 3 ,-1,0
       0      .1       0   284.5    .045       0   312.7      .1       0
#XS Ineff= 2 , 0
                          521.59         2386.91
Permanent Ineff=
       F       F
Bank Sta=284.5,312.7
XS Rating Curve= 0 ,0
Exp/Cntr(USF)=0,0
Exp/Cntr=0.3,0.1

Type RM Length L Ch R = 1 ,4234    ,599.1,608,616.6
XS GIS Cut Line= 5
2236487.97574611636530.6645273752236593.86045271636435.925579362
2236705.31803861636341.1866313492236780.55190909636005.420653831
2236852.99933992635910.681705818
#Sta/Elev= 30
       0 2415.91    63.5  2396.5   118.3 2386.92   150.4 2369.33   166.1 2364.71
   191.1 2363.57   219.5 2365.96   250.1 2365.63   304.2 2368.79   321.2 2367.45
   341.7 2370.01     354 2369.72   394.6 2364.61   444.1 2367.86  463.622360.682
   476.9 2360.51   484.4  2360.7   501.2 2362.64   526.1 2361.17   538.4 2364.79
   558.7 2365.06   572.1  2370.4   599.9 2387.57   620.4 2392.62   638.4 2400.97
   683.1 2408.74   703.7 2415.35   718.4 2416.07   728.4 2421.49   751.7 2425.79
#Mann= 4 ,-1,0
       0     .06       0      10      .1       0  463.62    .045       0
   484.4      .1       0
#XS Ineff= 2 , 0
           430.9 2379.43
Permanent Ineff=
       F       F
Bank Sta=463.62,484.4
XS Rating Curve= 0 ,0
Exp/Cntr(USF)=0,0
Exp/Cntr=0.3,0.1

Type RM Length L Ch R = 1 ,3626    ,346.2,338.2,327.2
XS GIS Cut Line= 3
 2236851.6061201636819.0610308862237316.94154122636402.488303593
2237390.78219188636245.054463512
#Sta/Elev= 30
       0 2408.47    38.8 2395.79    49.9 2394.45      98 2383.23   129.2 2378.48
   182.7 2359.56   242.4 2358.29   248.7 2359.29   308.7 2360.29   327.5  2358.1
   414.1 2359.39   434.6 2356.56   464.6 2359.25   503.1 2358.17   520.1 2353.89
   524.6 2353.51  555.05 2353.91   564.5 2355.31   569.8    2358   580.6 2365.63
   596.5 2382.05   602.1 2384.47   643.7  2391.8   661.1 2393.46   721.2 2404.39
   742.3 2410.55   754.6 2415.57   767.4 2416.71   778.3 2422.36   798.4 2429.09
#Mann= 3 ,-1,0
       0      .1       0   520.1    .045       0  555.05      .1       0
#XS Ineff= 2 , 0
          499.92 2380.71
Permanent Ineff=
       F       F
Bank Sta=520.1,555.05
XS Rating Curve= 0 ,0
Exp/Cntr(USF)=0,0
Exp/Cntr=0.3,0.1

Type RM Length L Ch R = 1 ,3288    ,546.2,547.9,548.4
XS GIS Cut Line= 4
2237525.92451478637125.5693921062237549.60925178636937.484715903
2237506.41943725636481.9018335452237535.67705355636311.929015051
#Sta/Elev= 30
       0 2436.75    16.5 2428.68    28.6  2424.9    36.7 2418.94    64.9 2416.76
    85.1 2403.49   137.5 2388.06   201.9 2351.69   234.1  2353.1   278.3  2350.3
   314.4 2353.94   358.6 2349.41   374.7 2352.43   386.8 2351.19   402.8 2354.21
   414.9 2352.24   451.7 2353.83  470.522350.027   475.2 2349.26   487.2 2350.03
   531.4 2353.53   579.6 2351.91   595.7 2367.11   623.8 2377.67   737.2 2405.97
   753.5 2410.94   769.7 2418.54   785.9 2419.76     794 2424.39   819.7  2432.1
#Mann= 5 ,-1,0
       0      .1       0      10     .06       0     110      .1       0
  470.52    .045       0   487.2      .1       0
#XS Ineff= 2 , 0
          230.58 2357.39
Permanent Ineff=
       F       F
Bank Sta=470.52,487.2
XS Rating Curve= 0 ,0
Exp/Cntr(USF)=0,0
Exp/Cntr=0.3,0.1

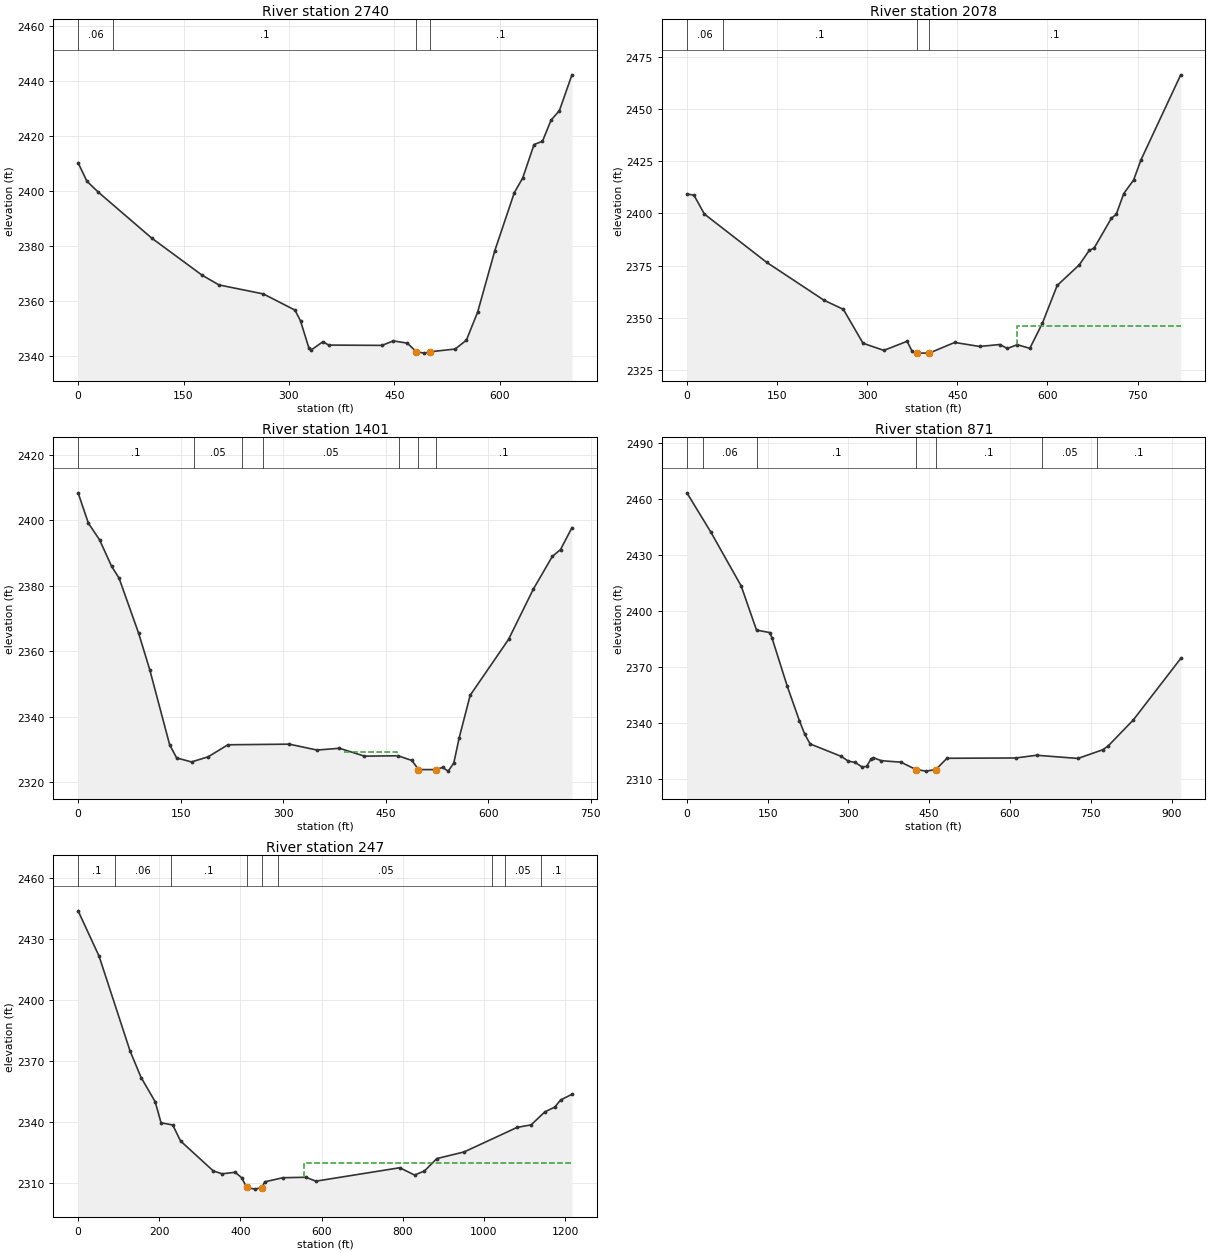
Type RM Length L Ch R = 1 ,2740    ,659.7,661.5,664.6
XS GIS Cut Line= 3
2237998.22603502637065.6609396852238009.37179361636491.654372311
2237998.22603502636363.478148528
#Sta/Elev= 30
       0 2410.23    12.5 2403.52    28.5  2399.6   104.5 2382.88   176.5 2369.32
   200.5 2365.79   263.7 2362.51   308.6 2356.64   316.5 2352.74   328.5 2342.77
     332 2342.18   348.5 2345.14   356.5 2343.91   432.6  2343.8   448.6 2345.43
   468.6 2344.61   481.2  2341.5   492.6 2340.98   500.8 2341.47   536.6 2342.47
   552.6 2345.69   568.6 2355.91   593.1  2378.3   620.8 2399.37   632.7 2404.67
   648.9 2416.87   660.9 2418.05     673  2425.7     685 2429.23   702.8 2442.22
#Mann= 4 ,-1,0
       0     .06       0      50      .1       0   481.2    .045       0
   500.8      .1       0
Bank Sta=481.2,500.8
XS Rating Curve= 0 ,0
Exp/Cntr(USF)=0,0
Exp/Cntr=0.3,0.1

Type RM Length L Ch R = 1 ,2078    ,676.3,677.1,676.4
XS GIS Cut Line= 4
2238383.03432344637168.1188689372238520.94518932636834.260738378
2238586.67722548636608.805797668 2238636.7851403636388.751269522
#Sta/Elev= 30
       0 2409.36    11.8 2408.72    29.1 2399.72     133 2376.54   228.2 2358.45
   260.4 2354.09   293.1 2337.86   327.8 2334.44   366.5  2338.8   374.8 2333.98
   382.92333.136   383.2 2333.13   403.62333.179   445.7 2338.25   487.1 2336.31
   520.7 2337.26   533.2 2335.37   549.8 2337.16   570.7 2335.43   591.5 2347.38
   616.2 2365.52   653.1 2375.42   669.5  2382.3   677.7 2383.42   706.4 2397.71
   714.6 2399.63     727 2409.53   743.4 2416.01   755.7 2425.67   821.8 2466.36
#Mann= 4 ,-1,0
       0     .06       0      60      .1       0   382.9    .045       0
   403.6      .1       0
#XS Ineff= 2 , 0
                          549.65         2346.19
Permanent Ineff=
       F       F
Bank Sta=382.9,403.6
XS Rating Curve= 0 ,0
Exp/Cntr(USF)=0,0
Exp/Cntr=0.3,0.1

Type RM Length L Ch R = 1 ,1401    ,527.6,530.2,532.8
XS GIS Cut Line= 3
2239077.36344794 637283.922663452239185.35534089636742.433940581
 2239191.6637652636572.461122087
#Sta/Elev= 30
       0 2408.38      15 2399.12    31.3 2394.07    48.9    2386    59.9 2382.34
    88.5 2365.55   104.8 2354.38   133.9 2331.49   144.1 2327.49   165.9 2326.26
   190.4 2327.85     219  2331.5   308.7 2331.69   349.5 2329.89   382.2 2330.44
   418.8 2328.03   467.8 2328.15   488.2 2326.71   497.8 2323.93  523.122323.927
     533 2324.59   541.2 2323.46   549.4 2325.92   557.4  2333.7   573.4 2346.61
   629.5 2363.66   665.5  2378.9   693.5 2388.98   705.5 2391.08   722.2 2397.74
#Mann= 7 ,-1,0
       0      .1       0     170     .05       0     240      .1       0
     270     .05       0     470      .1       0   497.8    .045       0
  523.12      .1       0
#XS Ineff= 1 ,-1
  389.27  466.76 2329.36
Permanent Ineff=
       F
Bank Sta=497.8,523.12
XS Rating Curve= 0 ,0
Exp/Cntr(USF)=0,0
Exp/Cntr=0.3,0.1

Type RM Length L Ch R = 1 ,871     ,631.4,624.3,612.3
XS GIS Cut Line= 4
2239657.43732346637344.1848154492239614.31036801637119.396067904
2239796.09506366636628.9395329752239696.90062679636497.043365353
#Sta/Elev= 30
       0 2463.29    44.7 2442.16   100.8 2413.45   129.3 2389.83   153.8 2388.52
   157.8 2385.86   186.3 2359.86   208.8 2341.44   218.9 2334.09   228.9 2328.92
   286.7 2322.26   299.5 2319.75   312.3 2319.04   325.4 2316.58   333.6 2316.92
   342.2 2320.96   346.4 2321.55   360.9 2319.96   397.6 2319.15  425.362315.217
   444.5 2314.37   462.4 2315.24   482.9 2321.25   610.9 2321.41   649.3 2322.87
   726.1 2321.16   771.8 2325.76   781.7 2327.67   828.9 2341.75     917 2374.66
#Mann= 7 ,-1,0
       0      .1       0      30     .06       0     130      .1       0
  425.36    .045       0   462.4      .1       0  658.89     .05       0
  761.95      .1       0
Bank Sta=425.36,462.4
XS Rating Curve= 0 ,0
Exp/Cntr(USF)=0,0
Exp/Cntr=0.3,0.1

Type RM Length L Ch R = 1 ,247     ,236.1,246.6,262.7
XS GIS Cut Line= 4
 2240017.0015596637361.0235423152240295.64552434637178.511745407
2240206.47945563636647.694992568 2240011.4286803636362.084928705
#Sta/Elev= 30
       0 2443.85    51.6 2421.59   128.1 2374.92   155.3 2361.89     190 2349.98
   204.4 2339.64   233.3 2338.56   252.4 2330.71   333.1 2315.99   354.7 2314.55
   387.2 2315.31   403.4 2312.55   415.6 2307.85   435.8 2307.02   452.4 2307.79
   460.2 2310.61   504.8 2312.63   561.6 2312.85   585.9 2310.93   792.8 2317.54
   829.3 2313.95   853.6 2315.93   884.1 2322.03   951.9 2325.34    1082 2337.37
  1116.6 2338.62  1150.5 2345.02  1174.7 2347.32  1189.2 2350.84  1217.2 2353.65
#Mann= 9 ,-1,0
       0      .1       0      90     .06       0     230      .1       0
   415.6    .045       0   452.4      .1       0   493.1     .05       0
 1021.35     .06       0 1051.35     .05       0 1141.35      .1       0
#XS Ineff= 2 , 0
                          556.29         2319.63
Permanent Ineff=
       F       F
Bank Sta=415.6,452.4
XS Rating Curve= 0 ,0
Exp/Cntr(USF)=0,0
Exp/Cntr=0.3,0.1