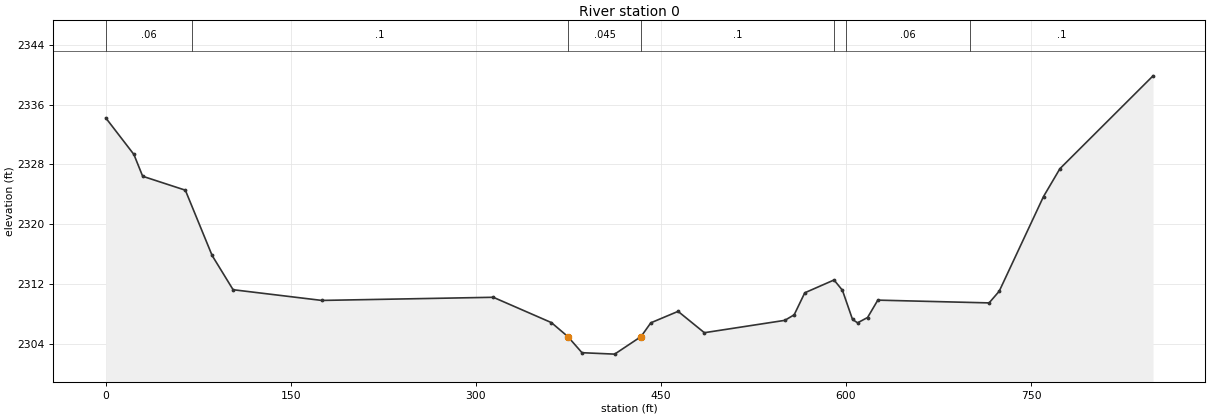
HEC-RAS study BIRCHFK.prj: BIRCHFK

--- BIRCHFK.g01 (geometry) --- (continued)

Type RM Length L Ch R = 1 ,0       ,288.2,288.2,288.2
XS GIS Cut Line= 4
2240258.64113314637337.6025822582240459.20992929 637268.52283901
2240593.52684935636914.9760034592240845.95678648 636858.80540227
#Sta/Elev= 30
       0 2334.21    22.8 2329.33    29.9 2326.42    64.5 2324.56    86.2 2315.84
   103.2 2311.27   175.1 2309.84   314.1 2310.26   361.2 2306.88  374.562305.011
     386 2302.86   412.5 2302.67  433.862305.011   441.8 2306.85   463.9 2308.38
   485.2 2305.53   550.4 2307.18     558 2307.92   566.6 2310.86   590.3 2312.57
   597.1  2311.2   605.3  2307.3   609.4 2306.85   617.5 2307.56   625.8 2309.88
     716 2309.51   724.2 2311.07   760.1 2323.71   773.4 2327.43   848.9 2339.83
#Mann= 7 ,-1,0
       0     .06       0      70      .1       0  374.56    .045       0
  433.86      .1       0  590.33     .05       0  600.33     .06       0
  700.33      .1       0
Bank Sta=374.56,433.86
XS Rating Curve= 0 ,0
Exp/Cntr=0.3,0.1
LCMann Table=0

Chan Stop Cuts=-1
Use User Specified Reach Order=0
Composite Channel Slope=5